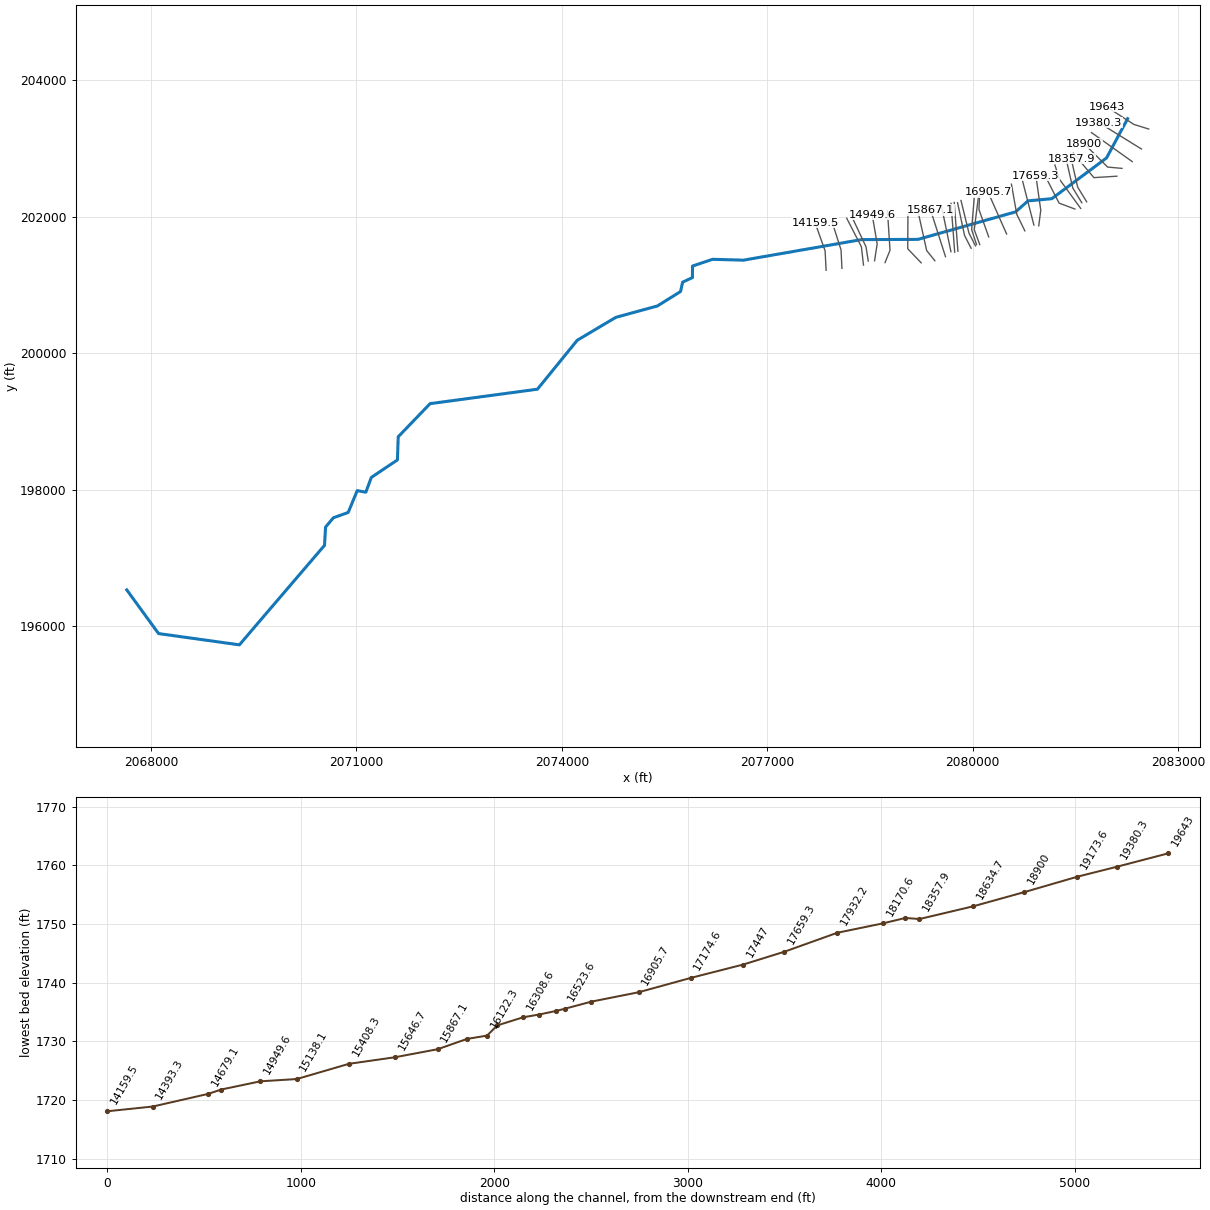
--- INDIANCKT2.prj (project) ---

Proj Title=INDIANCKT2
Current Plan=p01
Default Exp/Contr=0,0
English Units
Geom File=g01
Flow File=f01
Plan File=p01
BEGIN DESCRIPTION:
END DESCRIPTION:
DSS Export Rating Curves= 0
DSS Export Rating Curve Sorted= 0
DSS Export Volume Flow Curves= 0
DXF OffsetX= 0
DXF OffsetY= 0
DXF ScaleX= 0
DXF ScaleY= 0

--- INDIANCKT2.p01 (plan) ---

Plan Title=Floodplain
Program Version=4.00
Geom File=g01
Flow File=f01
K Sum by GR=0
Std Step Tol=0.01
Critical Tol=0.01
Num of Std Step Trials=20
Max Error Tol=0.3
Flow Tol Ratio=0.001
Split Flow NTrial=30
Split Flow Tol=0.02
Split Flow Ratio=0.02
Log Output Level=0
Friction Slope Method=1
Unsteady Friction Slope Method=2
Unsteady Bridges Friction Slope Method=1
Global Log Level=0
CheckData=False
Run HTab=0
Run UNet=0
Run PostProcess=0
UNET Theta=0
UNET Theta Warmup=0
UNET ZTol=0
UNET ZSATol=0
UNET MxIter=0
UNET MaxInSteps=0
UNET DtIC=0
UNET DtMin=0
UNET MaxCRTS=0
UNET WFStab=0
UNET SFStab=0
UNET WFX=0
UNET SFX=0
UNET DSS MLevel=0
UNET DZMax Abort=0
UNET Convert EG Bridges=0
UNET Use Existing IB Tables=0
UNET Froude Limit=0
UNET Froude Power=0
Write IC File=0
Echo Input=False
Echo Output=False
Write Detailed=0

--- INDIANCKT2.f01 (steady flow) ---

Flow Title=NFF Regression Equation
Program Version=4.10
Number of Profiles= 1
Profile Names=P100yr
River Rch & RM=INDIANCKT2,Main            ,19643
533.9789
River Rch & RM=INDIANCKT2,Main            ,18634.7
 555.072
River Rch & RM=INDIANCKT2,Main            ,18284.5
 590.727
River Rch & RM=INDIANCKT2,Main            ,15138.1
645.1587
River Rch & RM=INDIANCKT2,Main            ,14949.6
735.7274
River Rch & RM=INDIANCKT2,Main            ,14679.1
743.1907
River Rch & RM=INDIANCKT2,Main            ,10637.1
  820.94
River Rch & RM=INDIANCKT2,Main            ,10417.3
944.5469
River Rch & RM=INDIANCKT2,Main            ,5453.3
 1025.39
River Rch & RM=INDIANCKT2,Main            ,352.8
1138.052
River Rch & RM=INDIANCKT2,Main            ,182.2
1140.975
Boundary for River Rch & Prof#=INDIANCKT2,Main            , 1
Up Type= 0
Dn Type= 3
Dn Slope=0.013
DSS Import GetInterval= 0
DSS Import GetPeak= 0
DSS Import FillOption= 0

--- INDIANCKT2.g01 (geometry) ---

Geom Title=USGS 10m DEM
Program Version=4.10

River Reach=INDIANCKT2      ,Main
Reach XY= 30
     2082262.586      203437.458     2081953.371      202861.655
     2081154.621      202265.535     2080807.225      202233.244
     2080625.975      202072.306     2079200.487      201669.465
     2078374.845      201666.061     2076652.017      201365.015
     2076200.455      201377.515     2075908.267      201278.556
     2075907.085      201109.049     2075763.996       201043.14
     2075733.267      200905.119     2075394.725       200693.66
     2074787.955      200526.994     2074225.455      200192.098
     2073644.205       199474.91     2072076.182      199263.128
     2071610.871      198778.036     2071599.413      198438.973
     2071218.684      198182.723     2071137.955      197966.056
     2071011.913      197988.973     2070880.663      197669.181
     2070663.996      197591.056     2070549.934      197455.119
      2070534.83      197187.931     2069291.601      195730.119
     2068111.264      195895.105     2067647.058      196535.236

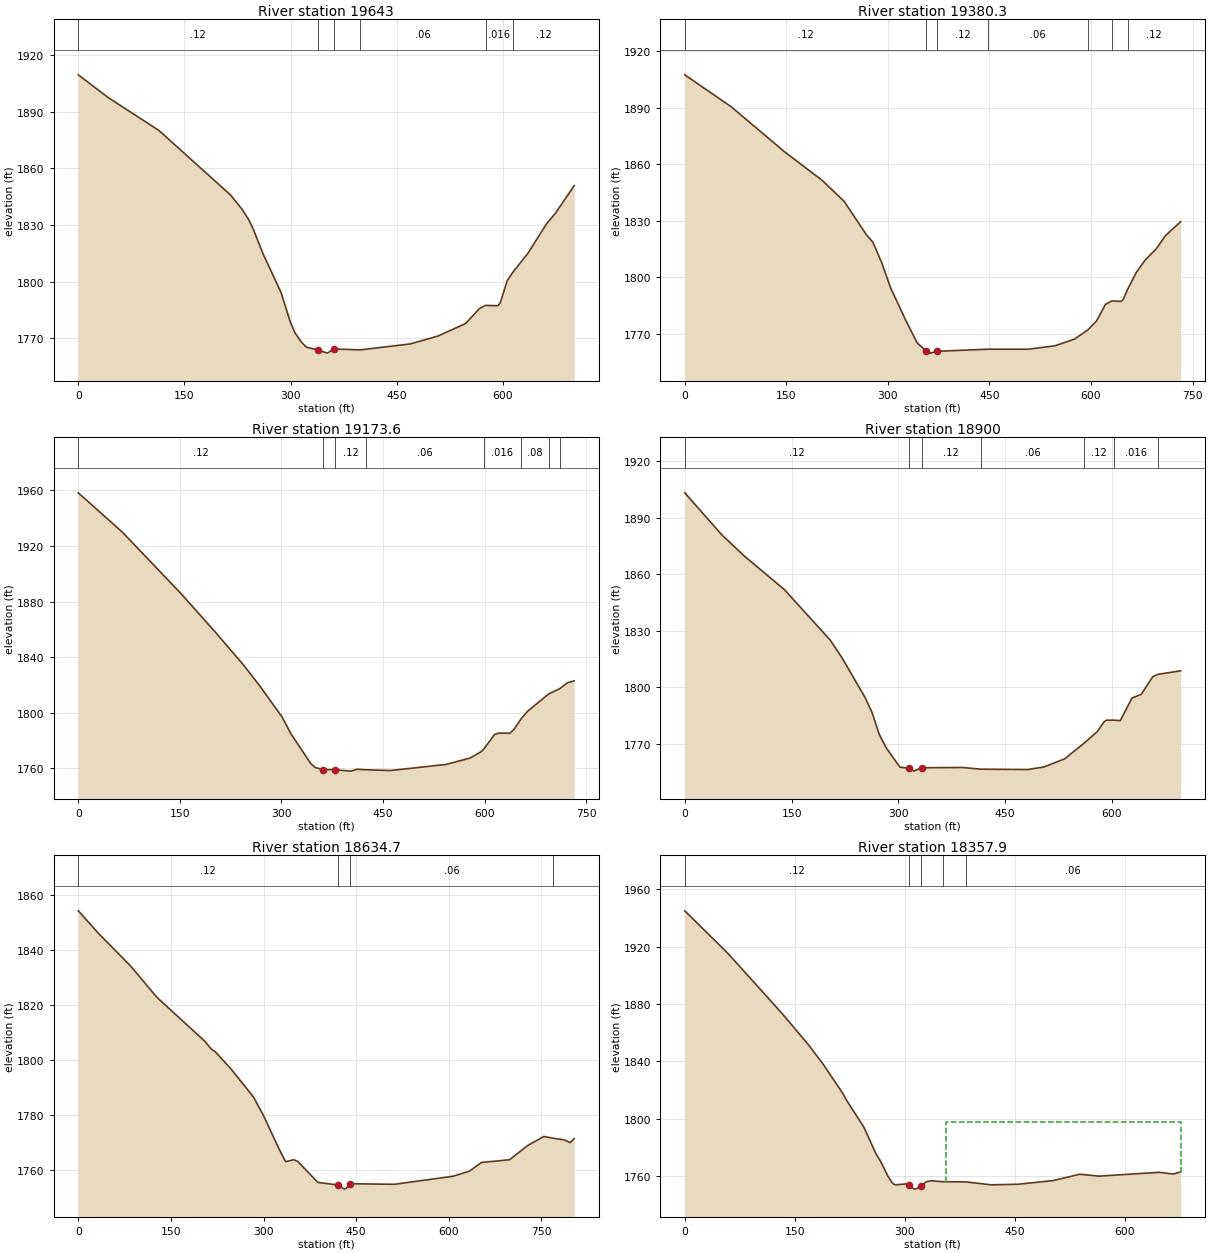
Type RM Length L Ch R = 1 ,19643   ,261.2,262.6,262.8
XS GIS Cut Line= 3
     2082570.246      203285.856     2082352.661      203353.628
     2081955.663      203610.509
#Sta/Elev= 30
       0  1909.7    42.3 1897.61     114 1880.16   214.9 1846.03   231.2 1838.51
   240.9 1832.78   247.5 1827.62   260.5 1815.24   286.6 1794.14   299.6 1778.63
   306.2 1772.82     316 1767.54   322.5  1765.2   338.8  1763.7   351.8 1762.04
   361.6 1764.24  398.261763.758   469.2 1766.92   508.4 1771.12   547.5 1777.77
     567 1785.72  575.491787.365   593.1 1787.21   596.4  1788.8   606.2 1800.53
  614.621805.171   635.5 1815.03   661.6 1830.56   674.7 1836.44   700.8  1850.9
#Mann= 6 ,-1 , 0
       0     .12       0   338.8    .045       0   361.6     .12       0
  398.26     .06       0  575.49    .016       0  614.62     .12       0
Bank Sta=338.8,361.6
XS Rating Curve= 0 ,0
Exp/Cntr=0.3,0.1

Type RM Length L Ch R = 1 ,19380.3 ,208,206.7,204.9
XS GIS Cut Line= 2
     2082464.227      202992.974     2081842.067      203379.284
#Sta/Elev= 30
       0 1907.55    68.7 1890.56   147.1 1866.76   202.7 1851.59   235.4 1840.36
   268.1  1822.7   277.9 1818.63     291 1807.68     304  1794.4   326.9 1776.77
   343.3 1765.15   356.4 1760.96   362.9 1759.78   372.7 1760.77  447.811761.858
   506.8 1761.85     546 1763.63   575.4 1767.17   595.61772.228   608.1 1776.85
   621.2 1785.64  630.371787.467   644.1 1787.25   647.3 1788.17  654.351793.911
     667 1802.68     680 1809.25   696.4 1815.18   709.4 1821.98   732.3 1829.57
#Mann= 7 ,-1 , 0
       0     .12       0   356.4    .045       0   372.7     .12       0
  447.81     .06       0   595.6     .12       0  630.37    .016       0
  654.35     .12       0
Bank Sta=356.4,372.7
XS Rating Curve= 0 ,0
Exp/Cntr=0.3,0.1

Type RM Length L Ch R = 1 ,19173.6 ,274.8,273.6,269.2
XS GIS Cut Line= 2
     2082329.807      202808.396     2081734.018      203234.128
#Sta/Elev= 30
       0 1958.16    65.4 1929.71   150.4 1886.37   202.7 1857.84   245.2 1833.67
   268.1 1819.24   300.8 1797.13   313.8 1785.07   343.2 1763.56   349.8 1760.69
     361 1759.23   379.2 1759.07   402.1 1758.06   411.9 1759.42  424.591759.034
   460.9  1758.5   542.7 1762.84   578.6 1767.45     595 1772.05  599.461774.285
   614.6 1784.36   621.1 1785.44   637.5 1785.27     644  1788.4  653.131795.167
   663.6 1801.12  694.781813.612  710.82 1817.28   722.5 1821.64   732.3 1822.94
#Mann= 8 ,-1 , 0
       0     .12       0     361    .045       0   379.2     .12       0
  424.59     .06       0  599.46    .016       0  653.13     .08       0
  694.78     .12       0  710.82     .06       0
Bank Sta=361,379.2
XS Rating Curve= 0 ,0
Exp/Cntr=0.3,0.1

Type RM Length L Ch R = 1 ,18900   ,262.9,265.3,260.2
XS GIS Cut Line= 3
     2082179.621      202709.467     2081969.552      202728.565
     2081626.376       203072.11
#Sta/Elev= 30
       0 1903.33    51.9 1881.04    84.4 1869.48   139.5 1852.06   204.4 1825.04
   220.7 1815.75   253.3 1794.55   263.1 1786.56   272.9 1775.24   282.6 1767.98
   302.2 1757.56   315.2 1757.01   321.7 1755.44   332.7 1757.23   390.2 1757.37
  415.521756.475   481.4  1756.3   504.2 1757.62   533.6 1761.97   561.3 1770.42
   579.2 1776.38     589 1781.66   592.2 1782.52  602.451782.507   611.8 1782.31
   628.1 1794.25   641.1 1796.24   657.4 1805.63  664.471806.849   696.5 1808.76
#Mann= 7 ,-1 , 0
       0     .12       0   315.2    .045       0   332.7     .12       0
  415.52     .06       0   561.3     .12       0  602.45    .016       0
  664.47     .06       0
Bank Sta=315.2,332.7
XS Rating Curve= 0 ,0
Exp/Cntr=0.3,0.1

Type RM Length L Ch R = 1 ,18634.7 ,281.9,276.7,263.9
XS GIS Cut Line= 3
     2082104.969      202594.884     2081769.899      202574.051
     2081468.844      202931.356
#Sta/Elev= 30
       0  1854.1    32.6 1845.92    84.7 1834.05   127.1 1822.71   205.3 1806.63
   215.1 1803.93   221.6 1802.94   247.7 1796.55   283.6 1786.49   299.9 1779.72
   325.9  1767.2   335.7 1762.98   348.8  1763.7   355.3 1763.09     388 1755.44
   420.7 1754.52   430.5 1753.01   433.7 1753.28   440.3 1754.96   512.2 1754.77
   606.9  1757.7     633 1759.51   652.6 1762.67   698.4 1763.69   727.8 1768.89
   753.9 1772.14   769.31771.483   786.6 1770.92   796.4 1769.91   802.9 1771.34
#Mann= 4 ,-1 , 0
       0     .12       0   420.7    .045       0   440.3     .06       0
   769.3    .016       0
Bank Sta=420.7,440.3
XS Rating Curve= 0 ,0
Exp/Cntr=0.3,0.1

Type RM Length L Ch R = 1 ,18357.9 ,73.3,73.5,73.3
XS GIS Cut Line= 3
     2081663.996      202219.884     2081532.052      202436.898
     2081438.302      202848.356
#Sta/Elev= 30
       0 1944.87    58.6 1915.32   133.5 1872.81   169.3 1851.06   188.8 1837.85
   214.9 1817.98   221.4 1812.14   244.2 1794.03   260.5 1775.63   267.1 1770.15
   276.9 1759.91   283.4 1754.83   286.7 1753.85     303 1754.51   306.3 1753.56
   312.9 1750.85   316.1 1751.15   322.7 1753.32   329.2    1756   335.8 1756.69
  352.471756.017  382.771755.923   417.5 1753.86   453.5 1754.22   502.6 1756.84
   538.6 1761.24   564.8 1759.91   646.5 1762.56   666.2 1761.37     676  1762.9
#Mann= 5 ,-1 , 0
       0     .12       0   306.3    .045       0   322.7     .12       0
  352.47     .08       0  382.77     .06       0
#XS Ineff= 2 , 0
                          355.74         1797.86
Permanent Ineff=
       F       F
Bank Sta=306.3,322.7
XS Rating Curve= 0 ,0
Exp/Cntr=0.3,0.1

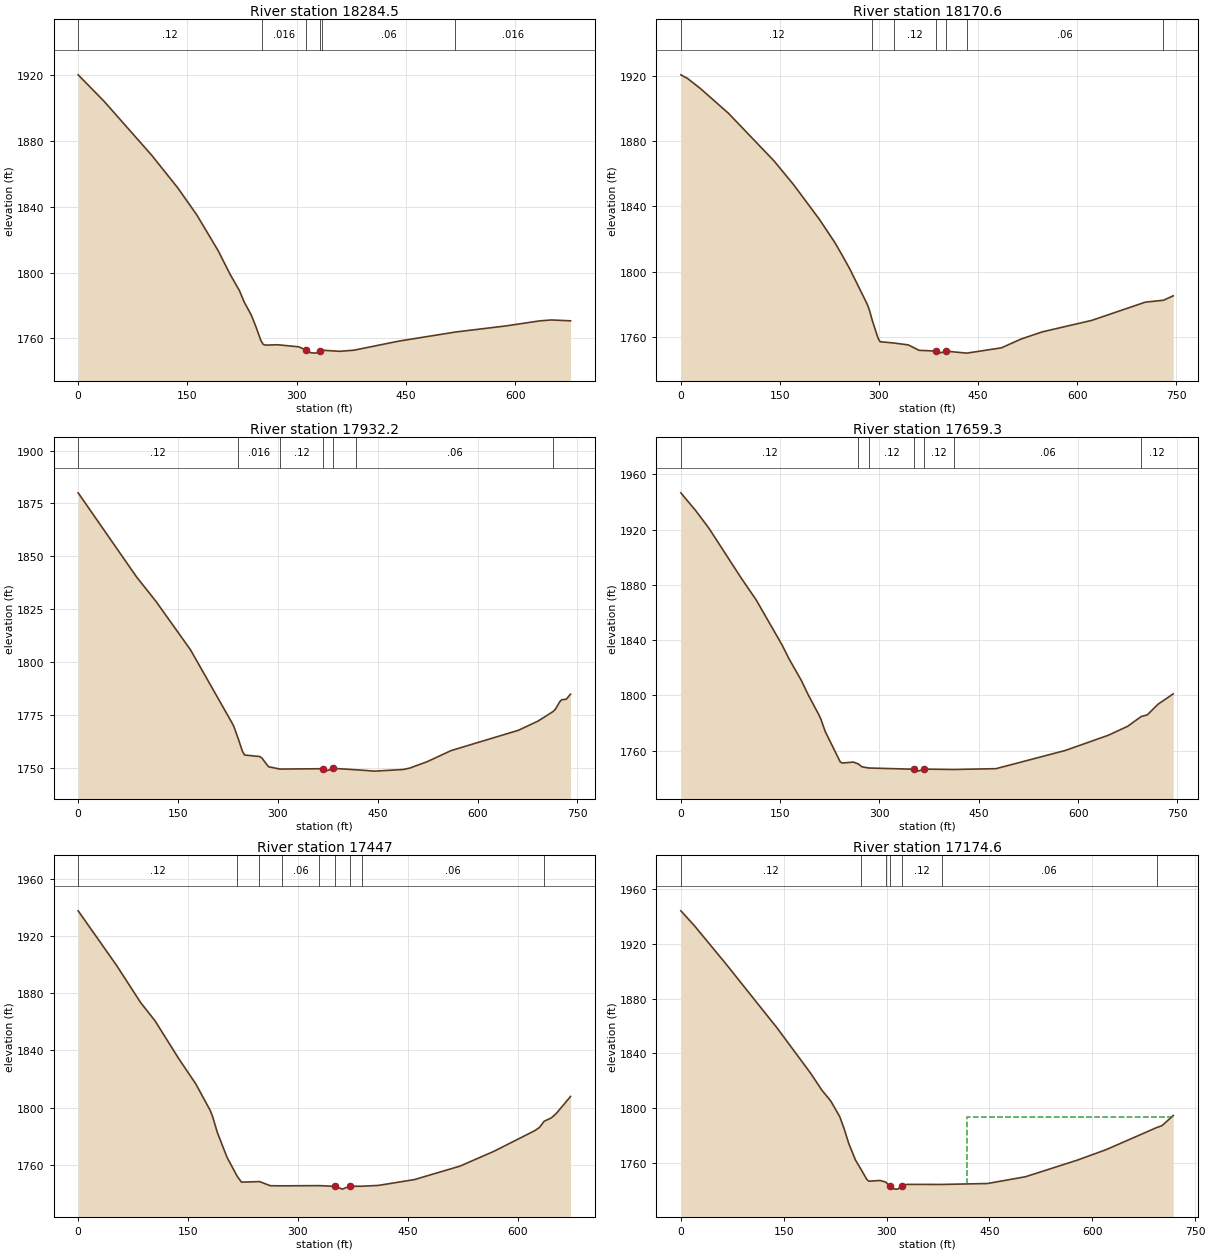
Type RM Length L Ch R = 1 ,18284.5 ,104.2,113.9,122.7
XS GIS Cut Line= 3
     2081592.816      202205.995     2081460.871      202423.009
     2081367.121      202834.467
#Sta/Elev= 30
       0  1920.2    35.8 1904.02   100.9 1871.35   136.8 1851.46   162.8 1835.11
   192.1  1813.4   208.4 1799.12   221.4 1789.04   227.9 1782.17   237.7 1774.16
   244.2 1766.93   250.7 1758.86  251.831758.018     254  1756.4   257.2 1755.89
   273.6 1756.12     303 1754.86   312.9 1752.87   319.4 1751.26     326 1751.03
   331.5 1752.37  334.881752.812   358.7 1752.13   378.3 1752.78   440.4 1758.34
  517.941763.856   587.6 1767.58   633.4 1770.62   649.8 1771.19     676 1770.66
#Mann= 6 ,-1 , 0
       0     .12       0  251.83    .016       0   312.9    .045       0
   331.5     .12       0  334.88     .06       0  517.94    .016       0
Bank Sta=312.9,331.5
XS Rating Curve= 0 ,0
Exp/Cntr=0.3,0.1

Type RM Length L Ch R = 1 ,18170.6 ,240.8,238.3,213.5
XS GIS Cut Line= 3
     2081576.464      202123.172     2081268.163      202548.009
     2081200.455      202758.079
#Sta/Elev= 30
       0 1920.63     9.8  1918.5    29.5 1912.28    72.2 1897.03   141.1 1867.89
   170.6 1853.41     210 1831.97   232.9 1818.07   242.8 1811.19   255.9 1801.66
   282.1  1780.2   285.4 1776.66  289.731770.407   298.6 1759.32   301.8  1757.1
  322.161756.336   344.5 1755.15   360.9 1751.83   385.8  1751.4   393.7 1750.32
   400.8 1751.36  432.621750.126   433.1 1750.12   485.6 1753.38   515.1 1758.74
   547.6 1763.18   622.3 1770.19   703.4 1781.36  730.661782.507   745.6 1785.22
#Mann= 7 ,-1 , 0
       0     .12       0  289.73    .016       0  322.16     .12       0
   385.8    .045       0   400.8     .12       0  432.62     .06       0
  730.66     .12       0
Bank Sta=385.8,400.8
XS Rating Curve= 0 ,0
Exp/Cntr=0.3,0.1

Type RM Length L Ch R = 1 ,17932.2 ,277.9,273,262.5
XS GIS Cut Line= 3
     2081492.121      202113.981     2081261.219      202200.787
      2081037.26      202640.023
#Sta/Elev= 30
       0 1880.02    87.6 1840.33   116.8 1828.76   168.8 1805.82   230.4 1771.72
   233.7 1769.75  240.661763.652   246.7 1757.95     250 1756.11   272.8  1755.4
   276.1 1754.67   285.9 1750.58  303.151749.474   368.5 1749.64     374 1748.74
   383.5 1749.81  417.231749.136   445.8  1748.5   488.3 1749.27   498.1 1749.93
   524.2 1752.94   560.1 1758.19   661.4  1767.8   690.7 1772.13  713.541776.688
   716.9 1777.76   723.4 1781.26   726.7 1782.28   733.2 1782.48   739.7 1784.86
#Mann= 7 ,-1 , 0
       0     .12       0  240.66    .016       0  303.15     .12       0
   368.5    .045       0   383.5     .12       0  417.23     .06       0
  713.54     .12       0
Bank Sta=368.5,383.5
XS Rating Curve= 0 ,0
Exp/Cntr=0.3,0.1

Type RM Length L Ch R = 1 ,17659.3 ,206.9,212.2,198.5
XS GIS Cut Line= 3
     2080964.344      201867.454     2080993.858       202096.62
     2080921.962      202604.063
#Sta/Elev= 30
       0 1946.58    22.8  1933.5    42.3 1921.05    91.1 1884.99   113.9 1869.02
     153 1836.44   162.7 1827.11   182.2 1810.65     192 1800.83   208.3 1786.15
   211.5 1782.86     218 1773.97   240.8 1751.88   244.1 1751.13   260.4 1751.82
  268.01 1750.49   273.5 1748.38  283.861747.528   352.3 1746.64   358.4 1745.27
   367.3 1746.73  412.481746.476   475.9 1747.04   580.4 1760.19   645.6 1771.22
     675 1777.75  695.311784.804   704.4 1785.95   720.7 1793.67   743.6 1801.16
#Mann= 7 ,-1 , 0
       0     .12       0  268.01    .016       0  283.86     .12       0
   352.3    .045       0   367.3     .12       0  412.48     .06       0
  695.31     .12       0
Bank Sta=352.3,367.3
XS Rating Curve= 0 ,0
Exp/Cntr=0.3,0.1

Type RM Length L Ch R = 1 ,17447   ,272.3,272.4,260.7
XS GIS Cut Line= 2
     2080893.163      201879.606     2080726.496      202530.648
#Sta/Elev= 30
       0 1937.45    52.4 1899.36    85.2 1873.44   104.9 1860.65   137.7 1833.89
   160.6 1816.54   180.3 1797.98   183.6 1793.59   190.1 1782.46   203.2 1765.28
  217.071752.049   222.9 1747.97  247.481748.343   262.3 1745.47  277.97 1745.39
  329.021745.531   350.8 1745.03   360.6 1743.09   370.4 1745.06  387.311745.125
   409.8 1745.69     459 1749.76   521.2 1759.17   567.1 1769.42   622.9 1783.85
   629.4 1786.08  636.031790.488   645.8 1792.87   652.4 1795.84     672  1807.8
#Mann= 9 ,-1 , 0
       0     .12       0  217.07    .016       0  247.48     .12       0
  277.97     .06       0  329.02     .12       0   350.8    .045       0
   370.4     .12       0  387.31     .06       0  636.03     .12       0
Bank Sta=350.8,370.4
XS Rating Curve= 0 ,0
Exp/Cntr=0.3,0.1

Type RM Length L Ch R = 1 ,17174.6 ,262.8,268.9,277.5
XS GIS Cut Line= 3
     2080761.219      201794.537     2080643.773       202035.04
     2080565.038      202478.565
#Sta/Elev= 30
       0 1944.23    19.6 1933.48    65.3 1905.75   140.4 1858.59   189.3 1825.51
   205.6  1813.2   218.7 1805.17   231.7 1793.82   238.3 1784.76   244.8 1774.32
   254.6 1762.15  263.441754.695   270.9 1748.11   274.2 1746.56   290.5 1747.13
  298.981745.956   304.5 1742.81   306.8 1741.54   313.4  1740.8   316.6 1740.84
   323.1 1743.44   329.7 1744.26  380.561744.224   447.2  1744.9   502.7 1749.86
   577.8 1761.92   620.2 1769.64     6941785.803   701.8 1787.23   718.1 1794.62
#Mann= 7 ,-1 , 0
       0     .12       0  263.44    .016       0  298.98     .12       0
   304.5    .045       0   323.1     .12       0  380.56     .06       0
     694     .12       0
#XS Ineff= 2 , 0
                          416.96         1793.45
Permanent Ineff=
       F       F
Bank Sta=304.5,323.1
XS Rating Curve= 0 ,0
Exp/Cntr=0.3,0.1

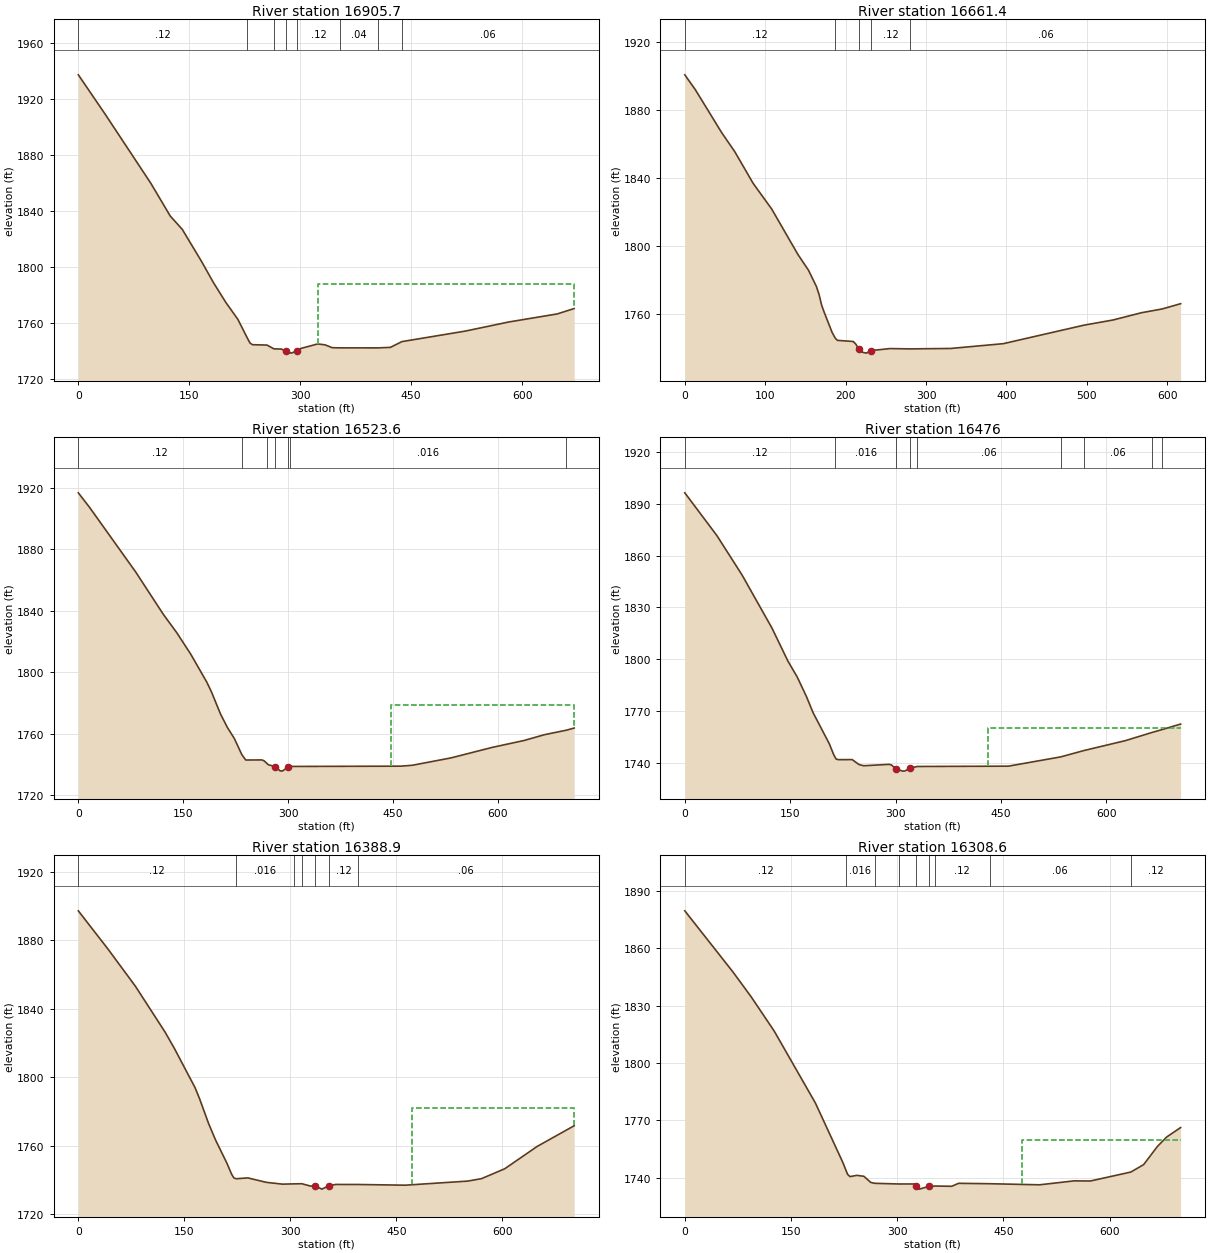
Type RM Length L Ch R = 1 ,16905.7 ,245.4,244.3,242.1
XS GIS Cut Line= 2
     2080494.954      201748.663     2080223.777      202361.811
#Sta/Elev= 30
       0 1937.18      36 1909.28    98.1 1859.64   124.3  1836.3   140.6 1826.72
   166.8 1803.68   183.1 1788.37   199.5 1774.54   215.8 1762.43  228.551749.085
   232.2 1745.53   235.5 1744.38   255.1 1744.12  264.431741.421   274.7 1741.26
   280.7 1739.53   287.8 1738.36   295.7 1739.93   300.9  1741.7   323.8 1744.94
   333.6 1744.27   343.4 1742.23  354.141742.127  405.29  1742.1   421.9 1742.48
  437.591746.593   523.3 1754.11   582.1 1760.62   647.6 1766.37   670.4 1770.21
#Mann= 8 ,-1 , 0
       0     .12       0  228.55    .016       0  264.43     .12       0
   280.7    .045       0   295.7     .12       0  354.14     .04       0
  405.29     .12       0  437.59     .06       0
#XS Ineff= 2 , 0
                          324.08          1787.5
Permanent Ineff=
       F       F
Bank Sta=280.7,295.7
XS Rating Curve= 0 ,0
Exp/Cntr=0.3,0.1

Type RM Length L Ch R = 1 ,16661.4 ,148.9,137.8,126.9
XS GIS Cut Line= 3
     2080233.441      201705.995      2080091.08      202107.037
      2080099.76      202298.009
#Sta/Elev= 30
       0 1900.69    13.1 1891.95    45.8  1866.7    62.2 1855.39    85.1 1836.69
     108 1821.71   140.8  1794.8   153.9 1785.57   163.7 1776.02     167 1771.28
   170.2 1765.02   173.5 1760.68   183.3 1748.87  187.211745.519   189.9 1744.28
   209.5 1743.61   212.8 1742.01   216.6    1739   219.3 1737.45   225.9 1736.76
   231.6 1738.26   255.3 1739.44  280.351739.254   330.6 1739.51   396.1 1742.33
   496.8 1753.26   532.5 1756.26   568.1 1760.57     594  1762.8   616.7 1765.88
#Mann= 5 ,-1 , 0
       0     .12       0  187.21    .016       0   216.6    .045       0
   231.6     .12       0  280.35     .06       0
Bank Sta=216.6,231.6
XS Rating Curve= 0 ,0
Exp/Cntr=0.3,0.1

Type RM Length L Ch R = 1 ,16523.6 ,44.5,47.5,51.2
XS GIS Cut Line= 3
     2080103.233      201593.148     2080022.388      201811.464
     2080082.283      202283.686
#Sta/Elev= 30
       0 1916.69    16.4 1907.02      82 1865.17   121.3 1837.74     141 1825.45
   160.7 1811.68   183.6  1793.5   190.2 1787.24   203.3 1772.68   213.1 1763.96
     223  1756.8  233.711746.315   239.3 1742.77   262.2 1742.83   265.4  1742.3
  269.781740.455   271.9 1739.64   281.7 1738.47   288.2 1735.79   291.5 1735.54
   299.6 1738.08   302.91738.585     461 1738.77   477.3 1739.34   532.8 1744.15
   591.4 1750.96   637.1 1755.47   666.4 1759.26  697.741762.186   708.8 1763.59
#Mann= 7 ,-1 , 0
       0     .12       0  233.71    .016       0  269.78     .12       0
   281.7    .045       0   299.6     .12       0   302.9    .016       0
  697.74     .06       0
#XS Ineff= 2 , 0
                          446.81         1778.27
Permanent Ineff=
       F       F
Bank Sta=281.7,299.6
XS Rating Curve= 0 ,0
Exp/Cntr=0.3,0.1

Type RM Length L Ch R = 1 ,16476   ,80.2,87.1,91.5
XS GIS Cut Line= 3
      2080055.49      201593.148     2079984.309      201813.634
     2080022.503      202285.856
#Sta/Elev= 30
       0 1896.29    45.7 1871.52    81.6 1848.63     124 1818.01   146.8 1798.82
   159.9 1789.71     173 1778.42   182.7 1768.87   205.6 1751.02   212.1 1744.49
  214.081743.056   215.4  1742.1   218.6  1741.8   238.2 1741.82     248 1738.94
   254.6 1738.26   290.5 1739.07   293.8 1738.79   300.3 1736.47   310.1 1735.15
   313.4 1735.25   319.9 1736.78  330.921737.848   460.4 1738.02  534.991743.401
     5681747.078     627 1752.81  664.381757.487  679.531759.249   705.5  1762.4
#Mann= 9 ,-1 , 0
       0     .12       0  214.08    .016       0   300.3    .045       0
   319.9    .016       0  330.92     .06       0  534.99     .08       0
     568     .06       0  664.38     .08       0  679.53     .06       0
#XS Ineff= 2 , 0
                          431.88         1759.86
Permanent Ineff=
       F       F
Bank Sta=300.3,319.9
XS Rating Curve= 0 ,0
Exp/Cntr=0.3,0.1

Type RM Length L Ch R = 1 ,16388.9 ,82.2,80.3,84.8
XS GIS Cut Line= 3
     2080040.733      201574.051     2079945.246      201761.551
     2079828.927      202238.981
#Sta/Elev= 30
       0 1897.14    42.1 1874.74    80.9 1853.02     123 1826.15     136 1816.73
   165.1 1793.94   171.6 1787.38   184.5 1772.75   194.2 1763.29   210.4 1749.62
     217 1743.25   220.2 1741.08  223.631740.613   239.9 1741.11   266.1 1738.51
     289 1737.46  305.01 1737.62  316.391737.705   328.4 1736.36   334.9  1736.5
   344.7 1734.55   354.6 1736.52   364.4 1737.29  396.211737.258   462.7 1736.85
   551.1 1739.24   570.8 1740.69   603.5 1746.44   649.4 1759.48   701.8 1771.57
#Mann= 7 ,-1 , 0
       0     .12       0  223.63    .016       0  305.01     .06       0
  316.39     .12       0   334.9    .045       0   354.6     .12       0
  396.21     .06       0
#XS Ineff= 2 , 0
                          471.68         1782.14
Permanent Ineff=
       F       F
Bank Sta=334.9,354.6
XS Rating Curve= 0 ,0
Exp/Cntr=0.3,0.1

Type RM Length L Ch R = 1 ,16308.6 ,135.4,134.4,94
XS GIS Cut Line= 3
     2079976.496      201539.329      2079881.01      201726.829
      2079778.58      202205.995
#Sta/Elev= 30
       0 1879.61      68 1847.66    93.9 1834.57   126.2  1816.8   184.5 1779.12
   223.5 1747.84  227.781743.794     230 1741.81   233.3 1740.64   243.1 1741.29
   252.9 1740.81   262.7  1737.6  268.271737.131  302.171736.777   324.8 1736.79
   327.2 1735.94   331.3 1734.09   344.3 1735.48  353.491735.715     377 1735.57
   386.8 1737.13  430.511736.919   501.1 1736.35   550.1 1738.41     573 1738.34
     6301743.015   648.1 1746.89   667.7 1756.44   680.8 1761.37   700.4 1766.28
#Mann= 9 ,-1 , 0
       0     .12       0  227.78    .016       0  268.27     .12       0
  302.17     .06       0   327.2    .045       0   344.3     .06       0
  353.49     .12       0  430.51     .06       0     630     .12       0
#XS Ineff= 2 , 0
                          475.75         1759.62
Permanent Ineff=
       F       F
Bank Sta=327.2,344.3
XS Rating Curve= 0 ,0
Exp/Cntr=0.3,0.1

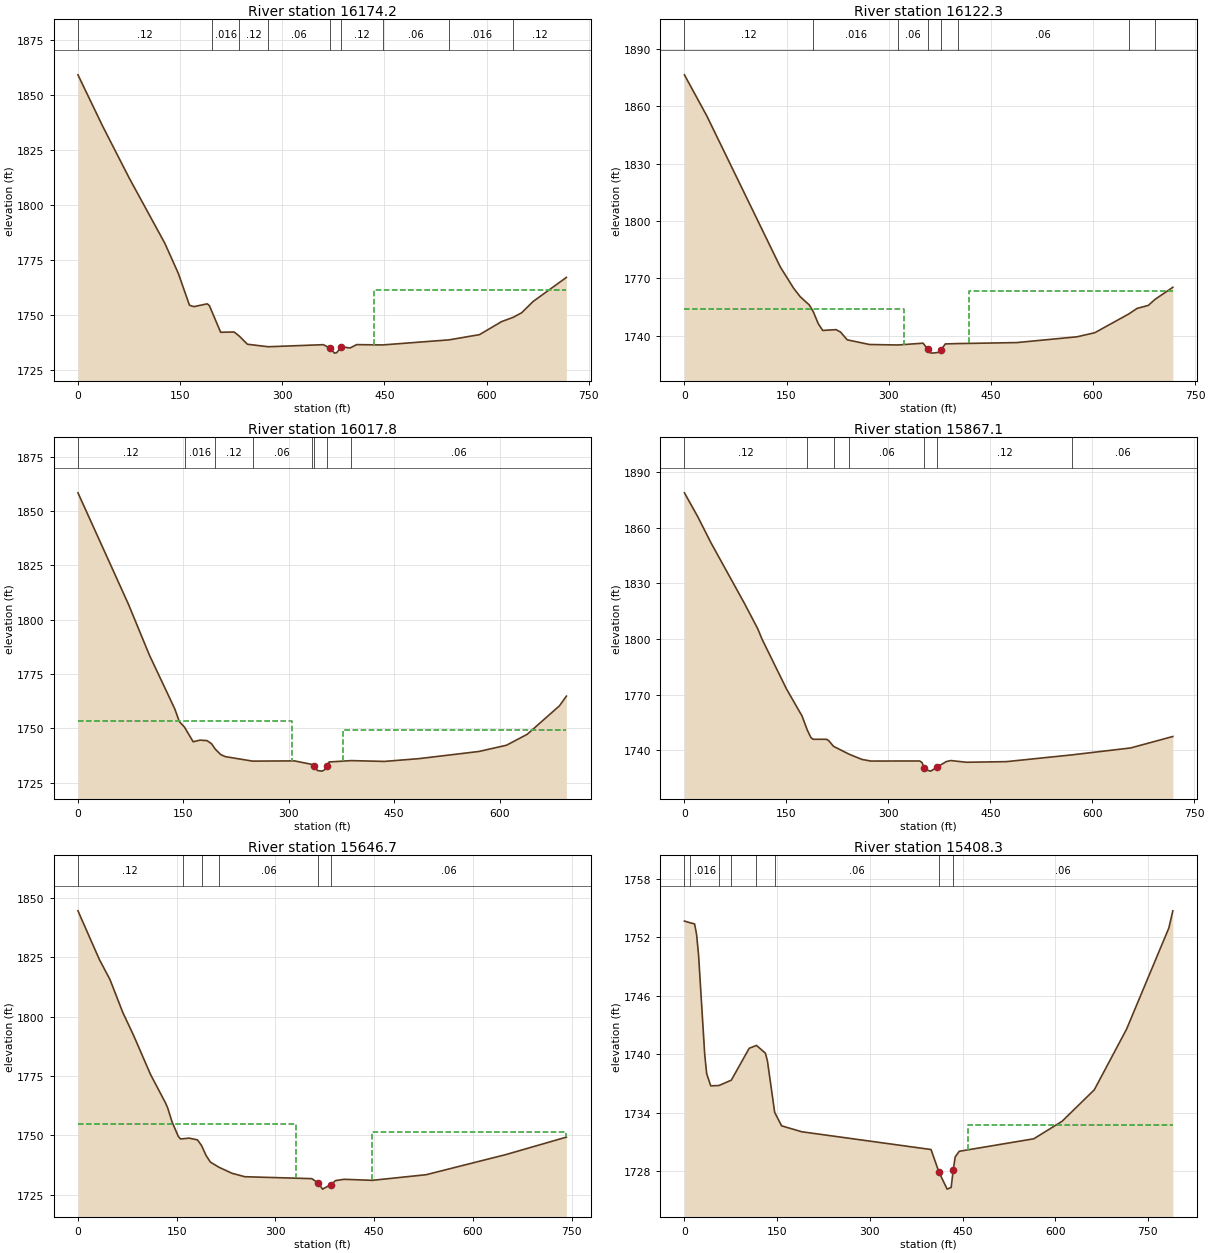
Type RM Length L Ch R = 1 ,16174.2 ,52.2,51.9,51.5
XS GIS Cut Line= 2
     2079783.788      201495.926     2079729.969      202211.204
#Sta/Elev= 30
       0 1859.26      36 1836.08    75.3 1812.31   127.7 1782.59   147.4 1768.97
   163.8 1754.47   170.3 1753.85     190 1755.12   193.2  1754.2  197.231751.217
   209.6 1742.18   229.3 1742.31  236.991740.432   248.9 1736.74  279.61  1735.6
   360.3 1736.54   370.1 1735.02   376.7  1732.7   379.9 1732.87   386.8 1735.57
   399.6 1735.04   409.4 1736.57   447.41736.424   544.71738.725   589.6  1741.1
   622.3 1747.05  639.171748.971   651.8 1751.09   668.2 1756.13   717.3 1767.13
#Mann= 9 ,-1 , 0
       0     .12       0  197.23    .016       0  236.99     .12       0
  279.61     .06       0   370.1    .045       0   386.8     .12       0
   447.4     .06       0   544.7    .016       0  639.17     .12       0
#XS Ineff= 2 , 0
                           434.6         1761.33
Permanent Ineff=
       F       F
Bank Sta=370.1,386.8
XS Rating Curve= 0 ,0
Exp/Cntr=0.3,0.1

Type RM Length L Ch R = 1 ,16122.3 ,101.4,104.5,106.6
XS GIS Cut Line= 2
     2079736.913      201482.037     2079683.094      202197.315
#Sta/Elev= 30
       0 1876.49    32.8 1855.07   140.8 1776.04   160.5 1764.84   170.3 1760.38
   183.4 1756.16  189.241752.637   196.5 1746.41   203.1 1742.84   222.7 1743.25
   229.3 1741.98   239.1 1737.93   271.8 1735.48  313.451735.232   350.5 1736.17
     357 1733.19   360.3 1731.26   363.6 1730.97   373.4 1731.35   377.1 1732.84
   383.2 1735.78  401.25 1735.96     488 1736.48   576.5  1739.5   602.7 1741.64
  652.41 1751.41   664.9 1754.37   681.3 1755.92  690.671758.956   717.3  1765.4
#Mann= 8 ,-1 , 0
       0     .12       0  189.24    .016       0  313.45     .06       0
     357    .045       0   377.1     .12       0  401.25     .06       0
  652.41    .016       0  690.67     .12       0
#XS Ineff= 2 , 0
          322.44  1754.1  418.32         1763.43
Permanent Ineff=
       F       F
Bank Sta=357,377.1
XS Rating Curve= 0 ,0
Exp/Cntr=0.3,0.1

Type RM Length L Ch R = 1 ,16017.8 ,146.9,150.6,152.8
XS GIS Cut Line= 2
      2079682.11      201488.547     2079541.485      202169.103
#Sta/Elev= 30
       0 1858.32    72.1 1806.92   101.6 1783.78   137.7 1759.04   144.2  1753.2
  151.661750.595   163.9 1743.91   173.7 1744.65   183.6 1744.42   190.1 1742.98
  195.291740.538   203.2 1737.98   209.8 1737.05  248.56    1735   308.1 1735.11
  332.671733.509   335.4 1732.65   340.9 1730.65   347.5  1730.4   350.7 1730.98
     354 1732.87   357.3 1734.61  388.731735.232     436 1734.86   485.1 1736.14
   570.4 1739.43   609.7  1742.3   639.2 1747.33   685.1 1760.43   694.9 1764.86
#Mann= 8 ,-1 , 0
       0     .12       0  151.66    .016       0  195.29     .12       0
  248.56     .06       0  332.67     .12       0   335.4    .045       0
     354     .12       0  388.73     .06       0
#XS Ineff= 2 , 0
          305.09  1753.5  377.11         1749.17
Permanent Ineff=
       F       F
Bank Sta=335.4,354
XS Rating Curve= 0 ,0
Exp/Cntr=0.3,0.1

Type RM Length L Ch R = 1 ,15867.1 ,222.4,220.4,218.4
XS GIS Cut Line= 2
      2079602.84      201415.522     2079384.483      202100.092
#Sta/Elev= 30
       0 1878.97    19.6 1866.09    39.2 1851.89    88.2 1819.32   107.8  1805.6
   114.3 1799.87   150.2 1773.02   173.1  1758.4  180.831750.791   186.2 1746.72
   189.4 1745.86     209 1745.85   212.3 1745.12  219.381742.042  242.611737.742
   261.3 1734.96   274.4 1734.09   346.2 1734.14   349.5 1733.32   352.7 1730.51
   355.9 1729.22   362.5 1728.65   372.3 1730.97   385.4 1733.83   391.9 1734.36
   414.8 1733.44   473.6 1733.77  570.51 1737.44   656.5 1741.17   718.6 1747.35
#Mann= 7 ,-1 , 0
       0     .12       0  180.83    .016       0  219.38     .12       0
  242.61     .06       0   352.7    .045       0   372.3     .12       0
  570.51     .06       0
Bank Sta=352.7,372.3
XS Rating Curve= 0 ,0
Exp/Cntr=0.3,0.1

Type RM Length L Ch R = 1 ,15646.7 ,243,238.4,232.9
XS GIS Cut Line= 3
     2079446.983      201357.037     2079327.191      201506.342
     2079208.884      202044.128
#Sta/Elev= 30
       0 1844.67    32.4 1824.22    48.7 1815.66    68.1 1801.82    84.4 1792.21
   110.3 1775.63     133 1763.66   136.3 1761.57   142.8 1755.77   152.5  1749.5
   155.7 1748.49  159.091748.505   168.7  1748.8   181.7 1748.05  187.871745.615
   194.7 1741.45   201.2 1738.69  214.111736.528     234 1733.97   253.7 1732.51
   355.3  1731.7   365.1 1729.86   371.7 1727.28   384.4 1729.22   391.4 1730.88
   404.5 1731.43   447.1 1730.99     529 1733.36   650.3 1741.86   742.1 1749.21
#Mann= 6 ,-1 , 0
       0     .12       0  159.09    .016       0  187.87     .12       0
  214.11     .06       0   365.1    .045       0   384.4     .06       0
#XS Ineff= 2 , 0
          331.03 1754.83  446.81         1751.17
Permanent Ineff=
       F       F
Bank Sta=365.1,384.4
XS Rating Curve= 0 ,0
Exp/Cntr=0.3,0.1

Type RM Length L Ch R = 1 ,15408.3 ,268.4,270.2,271.6
XS GIS Cut Line= 3
      2079247.33      201325.787     2079051.149      201532.384
     2079054.135      202037.809
#Sta/Elev= 30
       0 1753.64    9.471753.462    16.4 1753.35    19.6  1752.3    22.9 1750.16
    32.8 1739.99      36 1737.99    42.6 1736.75   55.781736.781   75.861737.329
   104.8  1740.6  116.59 1740.89     131  1740.1   134.3 1739.31  146.031734.035
   157.2 1732.65   189.9 1732.04     399 1730.22   412.1 1727.87   425.1 1726.16
   431.6 1726.33   434.9 1728.12   438.2 1729.47   444.7 1730.04   565.3 1731.32
     611 1733.11   663.2 1736.34   715.3 1742.54   783.8 1752.92   790.3 1754.69
#Mann= 8 ,-1 , 0
       0     .08       0    9.47    .016       0   55.78     .08       0
   75.86     .06       0  116.59    .016       0  146.03     .06       0
   412.1    .045       0   434.9     .06       0
#XS Ineff= 2 , 0
                          459.47         1732.75
Permanent Ineff=
       F       F
Bank Sta=412.1,434.9
XS Rating Curve= 0 ,0
Exp/Cntr=0.3,0.1

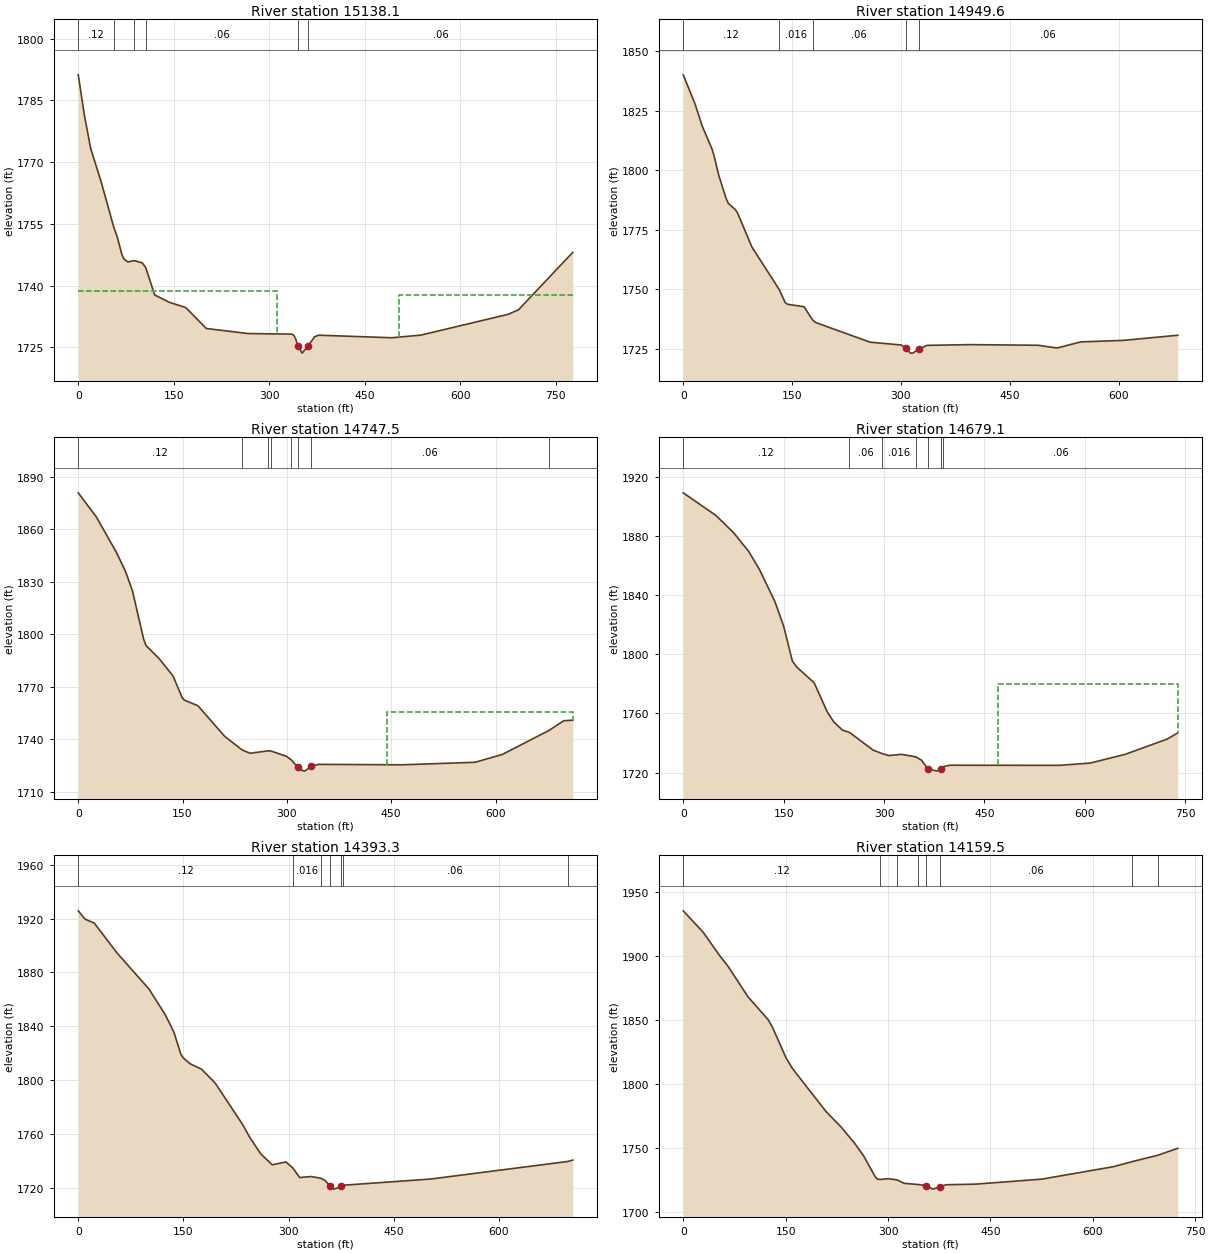
Type RM Length L Ch R = 1 ,15138.1 ,185.9,188.5,190.9
XS GIS Cut Line= 3
     2078719.552      201329.259     2078792.469      201509.815
     2078755.027      202090.978
#Sta/Elev= 30
       0 1791.22     9.7 1781.34    19.5 1773.33    35.7 1765.35   55.55 1754.32
    61.7 1751.59    68.2 1747.72    71.4 1746.49    77.9 1745.72   87.411746.057
   100.6 1745.51  105.981744.359   120.1  1737.7   142.8 1735.93   168.8 1734.65
   201.3 1729.55   266.7 1728.32   335.4 1728.18   338.7 1727.92     342 1726.91
   345.2 1725.21   351.8 1723.56   361.6 1725.39   371.4 1727.54   377.9 1727.92
   492.4  1727.3   538.2 1727.93   675.7    1733     692 1734.12   777.1 1748.06
#Mann= 6 ,-1 , 0
       0     .12       0   55.55     .06       0   87.41    .016       0
  105.98     .06       0   345.2    .045       0   361.6     .06       0
#XS Ineff= 2 , 0
          311.59 1738.67  503.34         1737.71
Permanent Ineff=
       F       F
Bank Sta=345.2,361.6
XS Rating Curve= 0 ,0
Exp/Cntr=0.3,0.1

Type RM Length L Ch R = 1 ,14949.6 ,195.8,202.1,209.3
XS GIS Cut Line= 3
     2078566.774      201356.169     2078604.969      201604.433
     2078532.013      202028.499
#Sta/Elev= 30
       0 1840.13    16.3 1827.84    26.1  1818.6    39.2 1809.29    42.4 1806.19
    48.9 1797.92    58.7 1788.46      62 1786.13    71.8 1783.47      75 1781.95
    94.6 1767.75   132.51749.781   140.3  1744.5   143.5 1743.72   166.4 1742.67
  178.181737.157   182.7    1736   257.7 1727.76   300.1  1726.6   306.6 1725.27
   313.1 1723.17   316.4 1723.17   324.2 1724.77   335.9 1726.44   394.6 1726.74
   489.2 1726.47   515.2 1725.32   547.8 1727.89   606.5 1728.53   681.5 1730.68
#Mann= 5 ,-1 , 0
       0     .12       0   132.5    .016       0  178.18     .06       0
   306.6    .045       0   324.2     .06       0
Bank Sta=306.6,324.2
XS Rating Curve= 0 ,0
Exp/Cntr=0.3,0.1

Type RM Length L Ch R = 1 ,14747.5 ,67,68.4,67.4
XS GIS Cut Line= 3
      2078474.76      201351.829     2078441.774      201560.162
     2078229.969      202013.287
#Sta/Elev= 30
       0 1880.94      26 1867.16    55.2 1846.64    68.2 1835.73    77.9 1824.94
    94.1 1797.14    97.4 1793.64   116.8 1785.88   136.3 1776.18   149.3 1763.88
   152.5 1762.38     172  1759.2   210.9 1741.53  235.731733.896   246.9 1731.99
   273.41733.373   277.21733.268   299.2 1730.27  306.341728.235   315.5 1723.96
   318.8 1722.49   325.4 1721.77   335.2 1724.45     345 1725.64   465.9 1725.39
   570.5 1726.82   609.8  1731.3  677.051745.067     698 1750.59   711.1 1750.89
#Mann= 8 ,-1 , 0
       0     .12       0  235.73    .016       0   273.4     .06       0
   277.2     .08       0  306.34     .06       0   315.5    .045       0
   335.2     .06       0  677.05    .016       0
#XS Ineff= 2 , 0
                          444.54         1755.36
Permanent Ineff=
       F       F
Bank Sta=315.5,335.2
XS Rating Curve= 0 ,0
Exp/Cntr=0.3,0.1

Type RM Length L Ch R = 1 ,14679.1 ,289.5,285.8,282.3
XS GIS Cut Line= 3
     2078405.156       201293.05     2078374.066      201561.898
     2078160.524      201978.565
#Sta/Elev= 30
       0 1909.01    48.9  1893.7      75 1882.15    97.8  1869.4   114.1    1857
     137 1835.44     150 1818.92     163 1795.38   169.6 1791.33   195.6 1780.64
   215.2    1761     225 1754.17     238 1748.68  248.011747.289   283.7 1735.22
  296.891732.902   306.7 1731.55   326.3 1732.35  347.341730.678   355.8 1728.47
   365.3 1722.73   378.7 1721.02   385.2 1722.78  388.381723.975   398.3    1725
     562 1724.92   607.9 1726.46   660.3 1732.37   722.5 1742.58   738.8 1746.83
#Mann= 7 ,-1 , 0
       0     .12       0  248.01     .06       0  296.89    .016       0
  347.34     .08       0   365.3    .045       0   385.2     .08       0
  388.38     .06       0
#XS Ineff= 2 , 0
                          470.32         1779.76
Permanent Ineff=
       F       F
Bank Sta=365.3,385.2
XS Rating Curve= 0 ,0
Exp/Cntr=0.3,0.1

Type RM Length L Ch R = 1 ,14393.3 ,233,233.8,234.4
XS GIS Cut Line= 3
     2078090.268      201245.228     2078077.191      201515.023
     2077945.246      201929.954
#Sta/Elev= 30
       0 1925.82     9.8 1919.61    22.8 1916.73    55.3 1894.49   100.9 1867.66
   123.7 1848.92   130.2 1842.25   136.7 1835.21   146.4 1819.15   149.7  1816.5
   159.5 1812.09   175.7 1808.14   195.3 1797.79   234.3 1767.09   244.1 1757.87
   260.4 1745.05   276.7 1736.97   296.3 1739.06  306.241734.581   315.9 1727.49
   332.3 1728.24  346.161726.935     352 1725.36   358.5 1721.52     365 1718.87
   375.3 1721.04  377.161721.738   502.6 1726.37   698.71739.463   705.5  1740.5
#Mann= 7 ,-1 , 0
       0     .12       0  306.24    .016       0  346.16     .08       0
   358.5    .045       0   375.3     .08       0  377.16     .06       0
   698.7    .016       0
Bank Sta=358.5,375.3
XS Rating Curve= 0 ,0
Exp/Cntr=0.3,0.1

Type RM Length L Ch R = 1 ,14159.5 ,259.5,255,250.7
XS GIS Cut Line= 3
     2077859.411       201217.26     2077844.552      201501.134
     2077696.983      201916.065
#Sta/Elev= 30
       0 1935.13    29.4 1918.28    52.3 1900.95    65.4 1892.04    94.8 1868.12
   124.2 1850.37   130.7  1844.4   150.3 1820.77   160.1 1812.07   209.1 1778.68
     232  1766.1   251.6 1753.48   264.7 1743.65     281 1727.94   284.3  1725.9
  288.081725.613   300.6 1726.17  313.211725.302   323.4 1722.62  344.561721.631
     356 1720.75   365.8 1718.07   375.6 1719.83   385.4  1721.5   427.8 1721.94
   525.7 1725.89     630 1735.54  657.791739.513  694.971744.447   724.6  1749.9
#Mann= 8 ,-1 , 0
       0     .12       0  288.08    .016       0  313.21     .12       0
  344.56     .06       0     356    .045       0   375.6     .06       0
  657.79    .016       0  694.97     .06       0
Bank Sta=356,375.6
XS Rating Curve= 0 ,0
Exp/Cntr=0.3,0.1