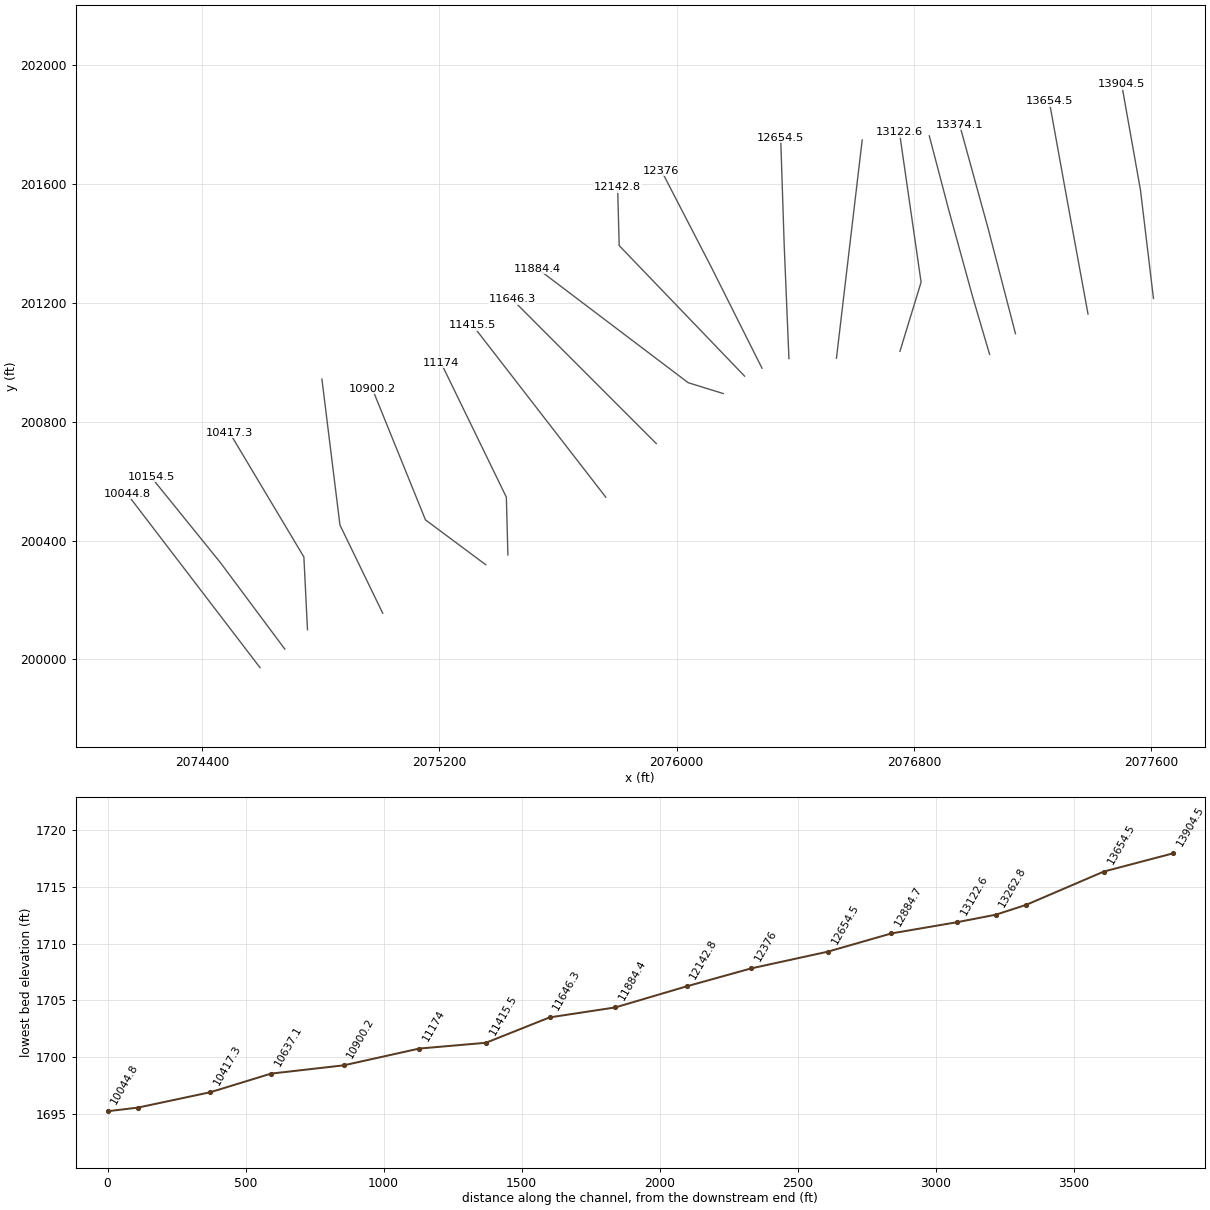
HEC-RAS study INDIANCKT2.prj: INDIANCKT2

--- INDIANCKT2.g01 (geometry) --- (continued)

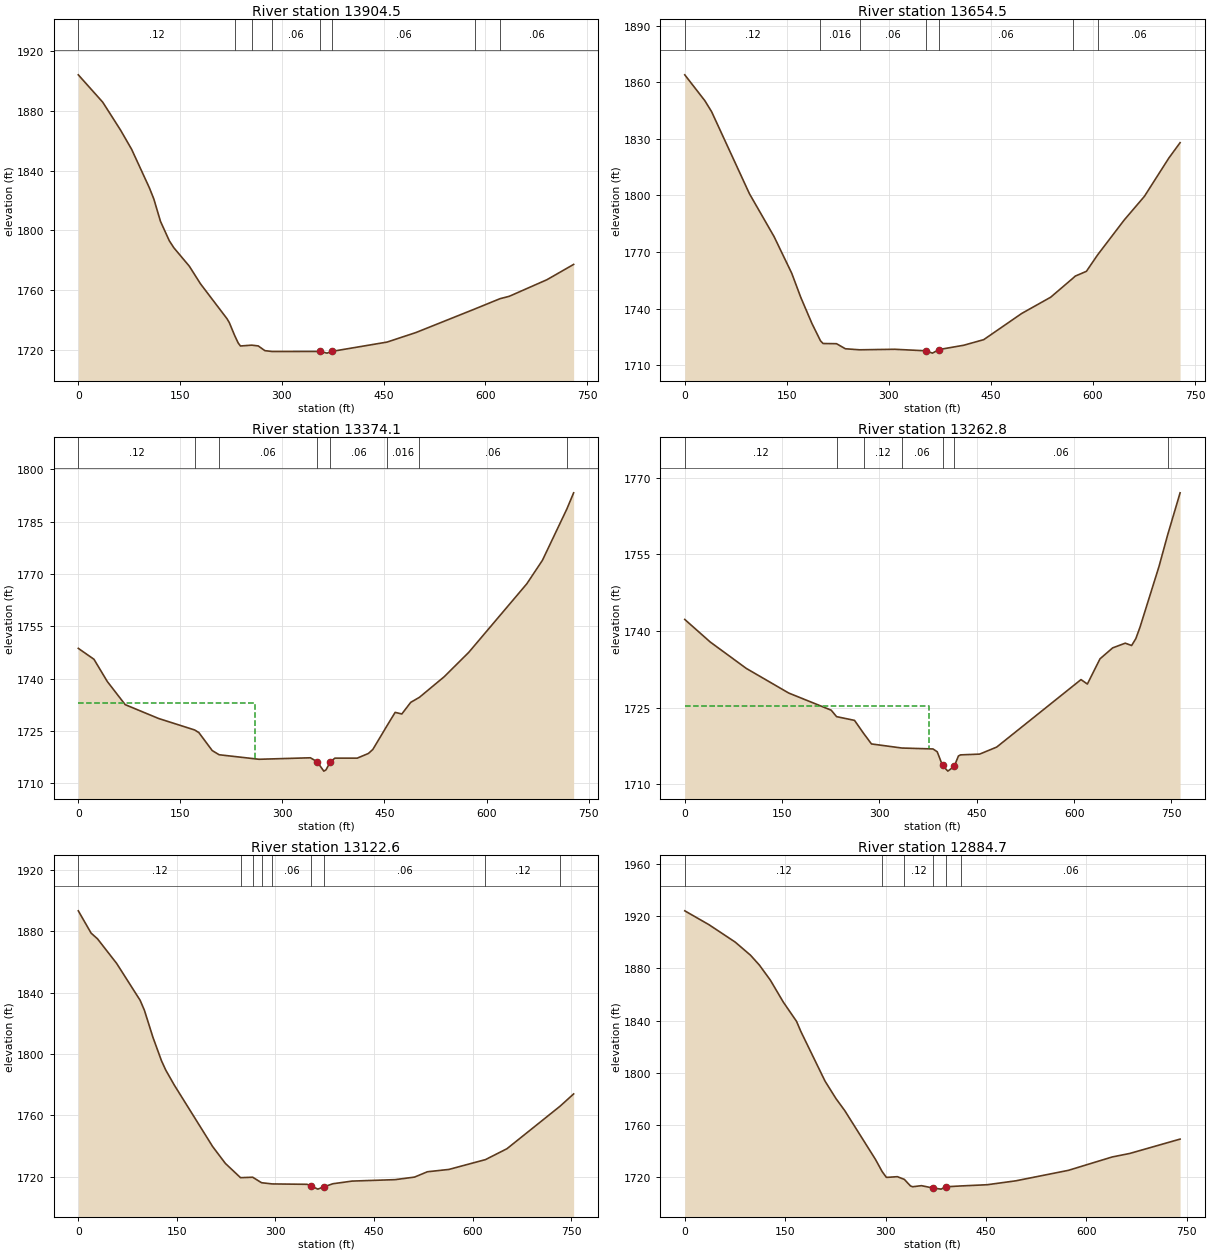
Type RM Length L Ch R = 1 ,13904.5 ,248.5,250,250
XS GIS Cut Line= 3
      2077606.83      201215.463     2077563.188      201579.499
     2077499.494      201937.361
#Sta/Elev= 30
       0 1903.95      36 1885.67    62.2 1867.07    78.6 1854.18   104.8  1828.4
   111.3 1821.02   121.1 1806.07   134.2    1793   140.8 1788.39   163.7 1776.03
     180 1764.35   219.3 1740.89   222.6 1738.34  230.231729.992   235.7 1724.73
     239 1722.74  255.671723.298   265.2 1722.78     275 1719.63  285.421719.058
   356.8  1719.1   366.6 1717.97   374.1 1719.15   455.1 1725.35   497.6 1731.72
  584.731747.526  621.591754.345   635.2 1755.94   690.8 1767.04   730.1 1777.25
#Mann= 8 ,-1 , 0
       0     .12       0  230.23    .016       0  255.67     .12       0
  285.42     .06       0   356.8    .045       0   374.1     .06       0
  584.73    .016       0  621.59     .06       0
Bank Sta=356.8,374.1
XS Rating Curve= 0 ,0
Exp/Cntr=0.3,0.1

Type RM Length L Ch R = 1 ,13654.5 ,278.5,280.3,282.2
XS GIS Cut Line= 3
     2077386.279      201163.001      2077320.57       201521.03
     2077255.732      201879.201
#Sta/Elev= 30
       0    1864    29.5 1850.28    39.4 1844.48    95.1 1800.89   131.2 1778.22
   154.1 1761.08   157.4 1758.56   170.5 1745.95   186.9  1732.1  199.421722.942
   203.3 1721.47     223 1721.37   236.1 1718.68  256.911718.133   308.3 1718.41
   354.2 1717.61     364 1716.37   373.8 1718.27   409.9 1720.54   439.4 1723.52
   495.2 1737.41   537.8 1746.03   569.91755.923   573.9 1757.22   590.3 1759.76
  606.751768.474     646 1787.05   675.5 1799.51   711.6 1819.92     728 1828.01
#Mann= 7 ,-1 , 0
       0     .12       0  199.42    .016       0  256.91     .06       0
   354.2    .045       0   373.8     .06       0   569.9    .016       0
  606.75     .06       0
Bank Sta=354.2,373.8
XS Rating Curve= 0 ,0
Exp/Cntr=0.3,0.1

Type RM Length L Ch R = 1 ,13374.1 ,111,111.4,111.4
XS GIS Cut Line= 3
     2077141.841      201096.818     2077050.147      201449.123
     2076953.632      201800.086
#Sta/Elev= 30
       0 1748.67      23 1745.54    42.6 1739.16    68.9 1732.52   118.1 1728.54
  170.911725.256   177.1 1724.52   196.8 1719.35  206.981718.138   265.6 1716.84
   341.1 1717.27   350.9 1716.16   360.8 1713.44     364 1713.79   370.4 1716.11
   377.2 1717.17     410 1717.17   426.4 1718.51   432.9 1719.66  453.831726.506
   465.7  1730.3   475.5 1729.84   488.6 1733.18  501.351734.619   537.8 1740.53
   573.9 1747.53   659.2  1767.2   682.1 1773.92  718.111788.683     728  1793.3
#Mann= 8 ,-1 , 0
       0     .12       0  170.91    .016       0  206.98     .06       0
   350.9    .045       0   370.4     .06       0  453.83    .016       0
  501.35     .06       0  718.11     .12       0
#XS Ineff= 2 , 0
          259.58 1732.98
Permanent Ineff=
       F       F
Bank Sta=350.9,370.4
XS Rating Curve= 0 ,0
Exp/Cntr=0.3,0.1

Type RM Length L Ch R = 1 ,13262.8 ,142.6,140.1,137
XS GIS Cut Line= 4
     2077054.621      201027.176      2076997.33       201221.62
     2076917.469      201511.551     2076851.381      201762.853
#Sta/Elev= 30
       0 1742.24    39.2 1737.83    94.8 1732.66   160.2 1727.84   225.6 1724.49
  233.931723.223   261.6 1722.49  275.771719.916   287.7 1717.88  334.641717.079
   382.5  1716.9     389 1716.35  397.16 1713.68   405.4 1712.56   415.2 1713.49
   421.7 1715.52     425 1715.74   454.4 1715.89   480.6 1717.26   610.6 1730.47
   620.4  1729.6   639.9 1734.54   659.4 1736.68   678.8  1737.6   688.6 1737.14
   695.1 1738.49   701.6 1740.76   730.8 1752.61  744.021758.743   763.3 1767.02
#Mann= 7 ,-1 , 0
       0     .12       0  233.93    .016       0  275.77     .12       0
  334.64     .06       0  397.16    .045       0   415.2     .06       0
  744.02     .12       0
#XS Ineff= 2 , 0
          376.26 1725.36
Permanent Ineff=
       F       F
Bank Sta=397.16,415.2
XS Rating Curve= 0 ,0
Exp/Cntr=0.3,0.1

Type RM Length L Ch R = 1 ,13122.6 ,243.3,237.9,231.5
XS GIS Cut Line= 3
     2076752.538      201037.592     2076823.719      201270.231
     2076750.802       201775.44
#Sta/Elev= 30
       0 1893.24    19.5 1878.71    29.2    1875    58.4 1858.94    94.1 1834.93
   100.6 1828.42   113.5 1810.91   126.5 1795.61     133 1789.52     146 1779.74
   204.4 1739.65   223.8 1728.64  246.851719.359  265.321719.655  278.771716.083
  295.171715.284     348 1715.04   354.5 1713.96   364.4  1711.9   374.2 1713.46
   387.3  1715.4   416.7 1717.14   482.2 1718.08   511.6 1719.74   531.2 1723.21
     564 1724.74  619.591731.139   652.3 1738.24  733.151765.962   753.7 1773.93
#Mann= 9 ,-1 , 0
       0     .12       0  246.85    .016       0  265.32     .12       0
  278.77    .016       0  295.17     .06       0   354.5    .045       0
   374.2     .06       0  619.59     .12       0  733.15     .06       0
Bank Sta=354.5,374.2
XS Rating Curve= 0 ,0
Exp/Cntr=0.3,0.1

Type RM Length L Ch R = 1 ,12884.7 ,229.6,230.3,234
XS GIS Cut Line= 2
     2076538.528      201014.284     2076625.317      201749.081
#Sta/Elev= 30
       0 1923.98      36 1913.41    75.3 1900.06    98.2    1890   111.3 1882.55
   127.7 1871.03   147.3 1854.02     167 1839.33   173.5 1831.51   209.5 1793.62
   225.9  1780.2     239 1771.01   284.8 1733.72  294.751724.423   301.2 1719.88
   317.6 1720.44  328.031718.344   337.2 1713.32   340.5 1712.73   353.6 1713.56
   370.7 1711.76     383 1710.91   389.6 1712.69  413.341713.365   451.8 1714.28
   494.4 1717.26   572.9 1725.27   638.4 1735.52   664.6 1738.21   739.9 1749.21
#Mann= 6 ,-1 , 0
       0     .12       0  294.75    .016       0  328.03     .12       0
   370.7    .045       0   389.6     .12       0  413.34     .06       0
Bank Sta=370.7,389.6
XS Rating Curve= 0 ,0
Exp/Cntr=0.3,0.1

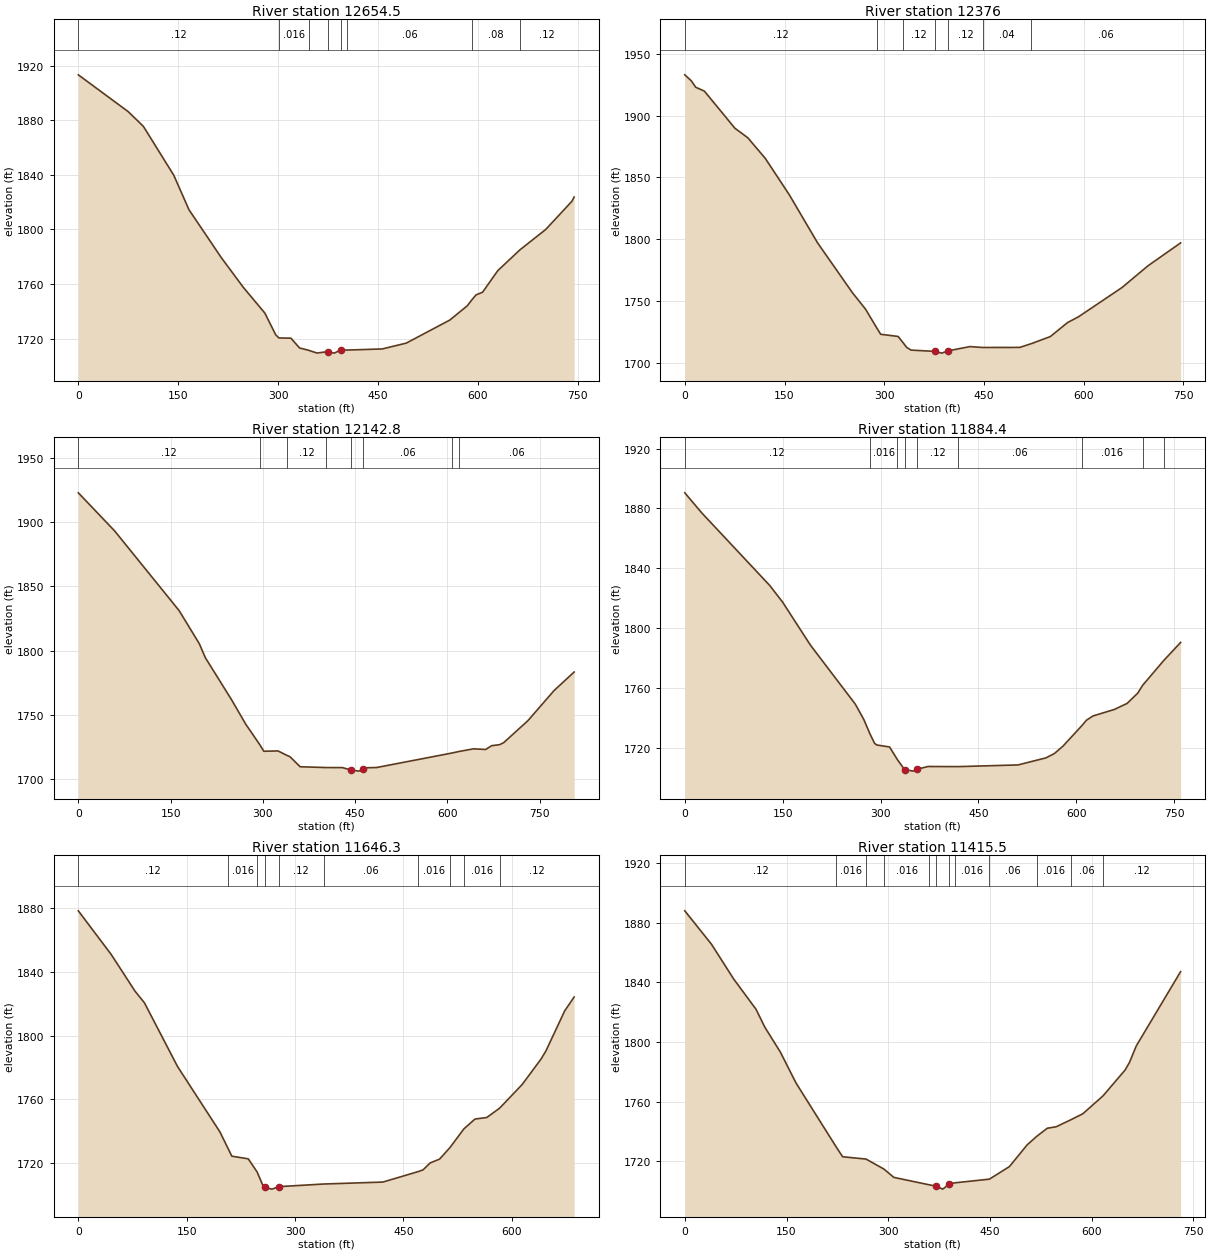
Type RM Length L Ch R = 1 ,12654.5 ,260,278.5,287.5
XS GIS Cut Line= 3
      2076378.41      201013.191     2076362.375      201397.306
     2076350.589       201757.33
#Sta/Elev= 30
       0 1913.34    74.9 1886.36    97.7 1875.57   143.4 1839.68   166.2 1814.42
     215 1779.13   247.6 1757.66   280.2 1738.62   296.5 1722.71  301.311720.421
   319.3 1720.26   332.3 1713.08  345.711711.417   358.4 1709.37   374.7 1710.41
   384.4  1709.3   394.3 1711.69  403.381711.535   456.5 1712.37   492.5 1716.63
     558 1733.56   584.2 1744.02  591.581748.681   597.3 1751.99   607.1 1753.94
     630 1769.78  663.31 1785.04   702.1 1800.01   741.4 1820.67   744.7 1823.73
#Mann= 8 ,-1 , 0
       0     .12       0  301.31    .016       0  345.71     .12       0
   374.7    .045       0   394.3     .12       0  403.38     .06       0
  591.58     .08       0  663.31     .12       0
Bank Sta=374.7,394.3
XS Rating Curve= 0 ,0
Exp/Cntr=0.3,0.1

Type RM Length L Ch R = 1 ,12376   ,219.9,233.2,239.4
XS GIS Cut Line= 3
     2076287.626      200980.657     2076115.748      201322.919
     2075948.973      201645.053
#Sta/Elev= 30
       0 1932.94     9.8 1928.09    16.4  1922.9    29.5 1919.75    75.3 1889.78
    94.9 1881.96   121.1 1865.32   157.1 1835.98   199.7 1797.03   252.1  1756.7
   271.7  1743.5  289.67 1727.36   294.6 1723.08   320.8 1721.31  328.051716.395
   333.9 1712.36   340.4 1710.26   376.4 1709.22   386.3 1707.82   396.1 1709.66
   428.8 1713.11  447.971712.379   503.9 1712.45   521.31715.513   549.7  1721.2
   575.8 1732.59   592.2 1737.24   657.5 1760.86   696.7 1778.49   745.7    1797
#Mann= 7 ,-1 , 0
       0     .12       0  289.67    .016       0  328.05     .12       0
   376.4    .045       0   396.1     .12       0  447.97     .04       0
   521.3     .06       0
Bank Sta=376.4,396.1
XS Rating Curve= 0 ,0
Exp/Cntr=0.3,0.1

Type RM Length L Ch R = 1 ,12142.8 ,258.3,258.4,260.7
XS GIS Cut Line= 3
     2076228.972       200953.86     2075806.358      201393.495
     2075801.149      201589.676
#Sta/Elev= 30
       0 1922.81      59 1893.19   163.9 1831.14   196.7 1805.39   206.6 1794.44
   249.2 1761.72   272.1 1742.84  295.271726.632   301.6 1721.71   324.6 1721.96
   339.51718.412   344.2 1717.41   360.6 1709.65  402.47 1709.03   429.5 1708.97
   442.6 1707.15   455.7 1706.24   462.3 1707.53   465.6  1708.8   485.2 1709.07
   608.11720.399  618.731721.508   642.5 1723.59   662.2 1723.09     672 1726.04
     685 1726.84   691.6 1728.42   730.8 1745.45   773.4 1768.92   806.1 1783.38
#Mann= 8 ,-1 , 0
       0     .12       0  295.27    .016       0   339.5     .12       0
  402.47     .06       0   442.6    .045       0   462.3     .06       0
   608.1    .016       0  618.73     .06       0
Bank Sta=442.6,462.3
XS Rating Curve= 0 ,0
Exp/Cntr=0.3,0.1

Type RM Length L Ch R = 1 ,11884.4 ,239.5,238.1,232.8
XS GIS Cut Line= 3
     2076157.052      200895.231     2076038.996       200931.69
     2075531.526       201315.52
#Sta/Elev= 30
       0 1890.41      26    1877   130.1 1828.52   149.8 1817.42   192.4 1788.68
   261.3 1749.15   274.4 1738.84  283.641729.386   290.8 1722.98   294.1 1721.86
   313.8 1720.52  325.761712.086   336.7 1705.46   349.9 1704.38   356.4 1705.69
   372.8 1707.48  419.171707.393   510.6 1708.52   553.2  1713.2   566.3 1716.12
   579.4 1721.02  608.271734.686   615.5  1738.4   625.4 1741.24   658.2  1745.6
   677.8 1749.64   694.2 1756.56  701.521761.693  733.641778.177   759.8  1790.4
#Mann= 9 ,-1 , 0
       0     .12       0  283.64    .016       0  325.76     .12       0
   336.7    .045       0   356.4     .12       0  419.17     .06       0
  608.27    .016       0  701.52     .06       0  733.64     .12       0
Bank Sta=336.7,356.4
XS Rating Curve= 0 ,0
Exp/Cntr=0.3,0.1

Type RM Length L Ch R = 1 ,11646.3 ,232.8,230.8,229.3
XS GIS Cut Line= 2
     2075931.358      200726.829     2075446.023      201212.217
#Sta/Elev= 30
       0 1878.48    45.8 1850.86    78.4 1828.02    91.5 1820.66   137.3 1780.63
   196.1 1739.41  207.171729.161   212.5 1724.23   235.3 1722.53  247.57 1714.23
     255 1706.36   258.2  1704.7     268  1703.5   277.8 1705.06   339.71706.711
   421.6 1707.94  470.811714.564   477.2  1715.6     487 1719.95   500.1 1722.38
  514.391729.587  533.86 1741.44   549.1 1747.55   565.5 1748.55  583.241754.412
   614.5 1769.32   640.6  1785.3   647.2 1790.28   673.3 1815.57   686.4 1824.32
#Mann= 10 ,-1 , 0
       0     .12       0  207.17    .016       0  247.57     .12       0
   258.2    .045       0   277.8     .12       0   339.7     .06       0
  470.81    .016       0  514.39     .06       0  533.86    .016       0
  583.24     .12       0
Bank Sta=258.2,277.8
XS Rating Curve= 0 ,0
Exp/Cntr=0.3,0.1

Type RM Length L Ch R = 1 ,11415.5 ,245.9,241.5,236.6
XS GIS Cut Line= 2
     2075761.219      200546.273     2075313.302      201124.398
#Sta/Elev= 30
       0 1887.95    39.4 1865.52    72.2 1842.14     105 1821.95   118.1 1809.86
     141 1793.16     164 1772.49  223.13 1729.68   232.8 1722.97  267.351721.427
  293.911714.657   308.3 1709.14  360.161704.189   370.6  1703.3   380.4 1701.26
   390.3 1704.74  398.831705.521  449.251707.944   478.8 1716.39     505 1730.98
  519.261736.734   534.6  1742.1   547.7 1743.09  569.451747.792     587 1751.79
  616.741763.765   649.4 1781.16   655.9 1786.27   665.8 1797.24   731.3 1847.18
#Mann= 12 ,-1 , 0
       0     .12       0  223.13    .016       0  267.35     .12       0
  293.91    .016       0  360.16     .12       0   370.6    .045       0
   390.3     .12       0  398.83    .016       0  449.25     .06       0
  519.26    .016       0  569.45     .06       0  616.74     .12       0
Bank Sta=370.6,390.3
XS Rating Curve= 0 ,0
Exp/Cntr=0.3,0.1

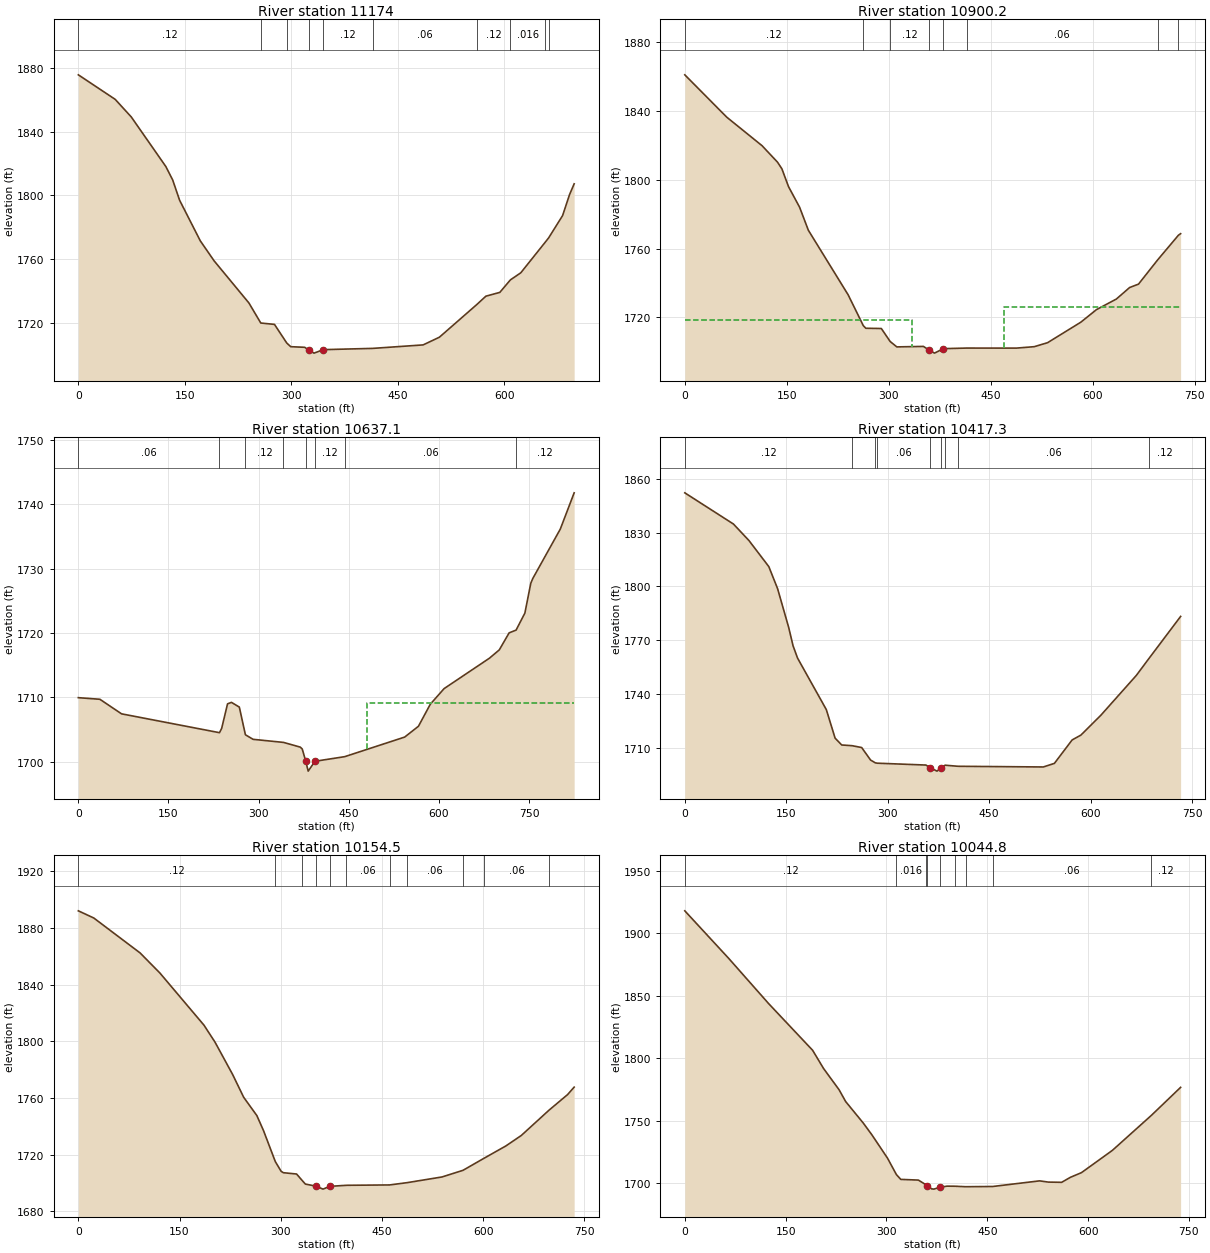
Type RM Length L Ch R = 1 ,11174   ,274.9,273.8,271.9
XS GIS Cut Line= 3
     2075431.358      200351.829     2075426.149      200546.273
     2075205.663      200999.398
#Sta/Elev= 30
       0 1875.73    51.9 1860.32    74.6 1849.23   123.2 1818.11   132.9 1809.65
   142.6 1796.92   171.8 1771.35   191.3 1758.75   240.3 1732.27  256.991719.683
   276.3 1718.81  293.641707.066   299.2  1704.8   318.9 1704.41   325.4 1702.43
     332 1700.75   345.3 1702.94  414.741703.731   485.7 1705.92   508.6 1710.76
  561.051731.217   574.1 1736.56   593.7 1738.94  608.621746.813   623.2 1751.25
  657.461770.379  662.441773.195   682.1 1787.22   691.9 1800.41   698.4 1807.19
#Mann= 10 ,-1 , 0
       0     .12       0  256.99    .016       0  293.64     .12       0
   325.4    .045       0   345.3     .12       0  414.74     .06       0
  561.05     .12       0  608.62    .016       0  657.46     .06       0
  662.44     .12       0
Bank Sta=325.4,345.3
XS Rating Curve= 0 ,0
Exp/Cntr=0.3,0.1

Type RM Length L Ch R = 1 ,10900.2 ,268.9,263.1,257.1
XS GIS Cut Line= 3
     2075356.705      200318.842      2075153.58      200469.884
     2074974.619      200910.929
#Sta/Elev= 30
       0    1861    61.7 1836.39   113.6 1819.82   136.3 1810.26   142.8 1806.37
   152.5 1796.06   168.8 1784.07   181.7 1770.67   240.2 1733.16  262.461715.269
   266.2 1713.72     289 1713.58  301.991706.026   311.8 1702.89   350.9 1703.17
   358.5 1701.23   367.2 1699.27   380.3 1701.87  414.341702.205   487.8 1702.19
   513.9 1703.02   533.5 1705.34   582.4 1717.26   605.2 1724.51   634.6  1730.7
   654.1 1737.39   667.2 1739.38  695.411753.492  725.871767.789   729.1 1768.68
#Mann= 8 ,-1 , 0
       0     .12       0  262.46    .016       0  301.99     .12       0
   358.5    .045       0   380.3     .12       0  414.34     .06       0
  695.41     .08       0  725.87    .016       0
#XS Ineff= 2 , 0
          333.75 1718.33  469.42         1725.95
Permanent Ineff=
       F       F
Bank Sta=358.5,380.3
XS Rating Curve= 0 ,0
Exp/Cntr=0.3,0.1

Type RM Length L Ch R = 1 ,10637.1 ,208.6,219.8,229
XS GIS Cut Line= 3
     2075009.483      200155.648     2074865.385      200452.523
     2074804.621      200943.842
#Sta/Elev= 30
       0 1709.95    35.9  1709.7    71.9 1707.44  234.891704.512   238.5 1705.17
   248.3 1708.99   254.8 1709.22   267.9 1708.49  278.041704.188   290.8 1703.48
  341.381703.002   369.3 1702.27   372.6 1701.98  378.25 1700.15   382.5 1698.54
   393.8 1700.07  443.281700.786   543.1 1703.83     566 1705.51   585.7 1708.93
   608.7 1711.36   684.1 1716.08   700.5 1717.37   716.9 1720.02  728.431720.444
   743.1 1723.09   752.9 1727.71   756.2 1728.45   802.1 1736.15   825.1 1741.77
#Mann= 8 ,-1 , 0
       0     .06       0  234.89    .016       0  278.04     .12       0
  341.38     .06       0  378.25    .045       0   393.8     .12       0
  443.28     .06       0  728.43     .12       0
#XS Ineff= 2 , 0
                          481.06         1709.14
Permanent Ineff=
       F       F
Bank Sta=378.25,393.8
XS Rating Curve= 0 ,0
Exp/Cntr=0.3,0.1

Type RM Length L Ch R = 1 ,10417.3 ,258.7,262.8,265.9
XS GIS Cut Line= 3
      2074756.01      200100.092     2074743.858      200344.884
     2074493.511      200763.674
#Sta/Elev= 30
       0 1852.15    71.9 1834.75    94.8 1825.56   124.2    1811   137.2 1798.67
   153.6 1777.04   160.1 1766.76   166.7 1759.95   209.2 1731.24   222.2  1715.3
     232 1711.48  247.33 1711.09   261.5 1710.06   274.6  1703.1  281.621701.532
  284.41 1701.33   356.4 1700.29   362.8 1698.86   372.8  1696.9   379.4 1698.92
  384.851700.207  403.881699.602     530 1699.22   546.4 1701.22   572.6 1714.29
   585.6 1717.01   615.1 1728.08   667.5 1750.28   685.91759.605     733  1783.2
#Mann= 9 ,-1 , 0
       0     .12       0  247.33    .016       0  281.62     .12       0
  284.41     .06       0   362.8    .045       0   379.4     .06       0
  384.85     .12       0  403.88     .06       0   685.9     .12       0
Bank Sta=362.8,379.4
XS Rating Curve= 0 ,0
Exp/Cntr=0.3,0.1

Type RM Length L Ch R = 1 ,10154.5 ,109.2,109.7,109.2
XS GIS Cut Line= 3
     2074679.529      200034.818     2074462.836      200325.504
     2074228.691      200614.734
#Sta/Elev= 30
       0  1892.2    22.9 1887.13    91.5 1862.46   120.9 1848.24   186.2 1811.39
   202.5 1799.44   228.6  1776.6     245 1760.45   264.6 1747.47   274.4 1736.89
  291.881715.004   300.5 1708.14   303.8 1707.14   323.4 1706.22  331.731701.633
   336.4 1699.12   352.8 1697.58   362.6 1695.54   372.4 1697.49  397.041698.244
  461.231698.499  487.561700.136   538.8 1704.13  570.031708.836  600.831717.261
   633.5 1726.05   656.4 1733.46  697.231751.233   724.9 1762.32   734.7 1767.61
#Mann= 11 ,-1 , 0
       0     .12       0  291.88    .016       0  331.73     .12       0
   352.8    .045       0   372.4     .12       0  397.04     .06       0
  461.23    .016       0  487.56     .06       0  570.03     .12       0
  600.83     .06       0  697.23     .12       0
Bank Sta=352.8,372.4
XS Rating Curve= 0 ,0
Exp/Cntr=0.3,0.1

Type RM Length L Ch R = 1 ,10044.8 ,65.8,65.8,65.6
XS GIS Cut Line= 2
     2074596.046      199972.269     2074147.756       200558.04
#Sta/Elev= 30
       0 1918.11    65.6 1879.86   124.6 1843.88   190.1 1806.45   206.5 1791.77
   229.5 1774.83   239.3 1765.37   265.6 1748.07   278.7 1738.42   301.6 1719.99
  314.821706.849   321.3 1703.02   347.5 1702.45  359.341698.503   360.6 1697.98
   367.2 1695.44   370.4 1695.22   379.1 1696.63   390.1 1697.61  401.731697.548
  417.741697.152  458.031697.329   527.8 1701.84   540.9 1700.85   560.6 1700.67
   573.7 1704.69   590.1 1708.42     636 1726.22  694.191754.337   737.6 1776.74
#Mann= 9 ,-1 , 0
       0     .12       0  314.82    .016       0  359.34     .12       0
   360.6    .045       0   379.1     .12       0  401.73     .06       0
  417.74    .016       0  458.03     .06       0  694.19     .12       0
Bank Sta=360.6,379.1
XS Rating Curve= 0 ,0
Exp/Cntr=0.3,0.1