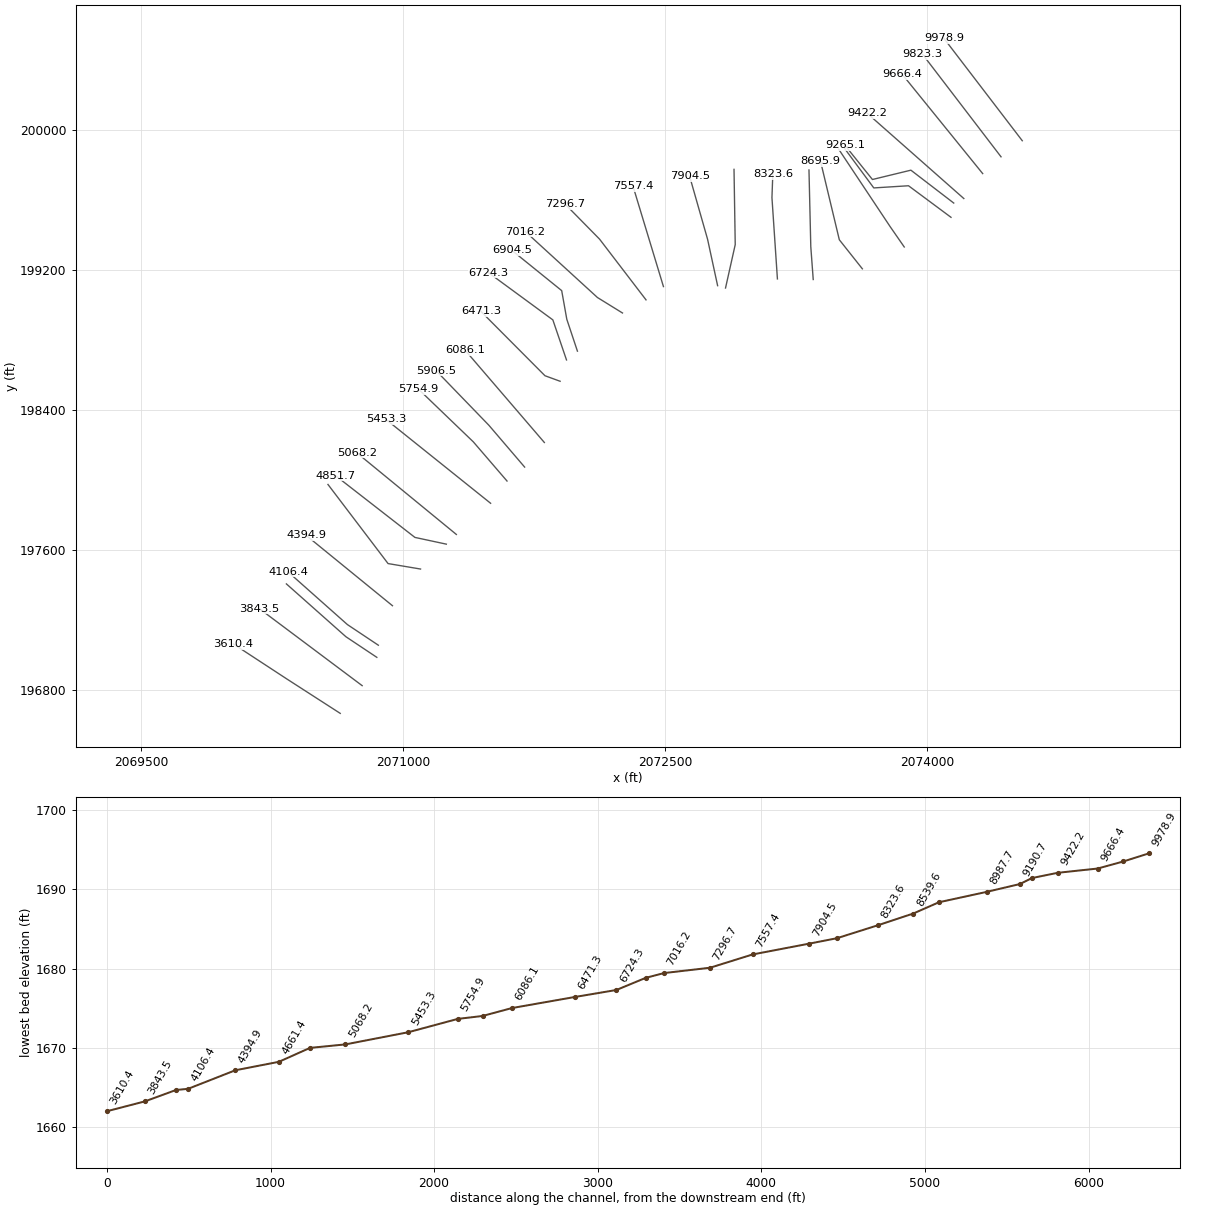
HEC-RAS study INDIANCKT2.prj: INDIANCKT2

--- INDIANCKT2.g01 (geometry) --- (continued)

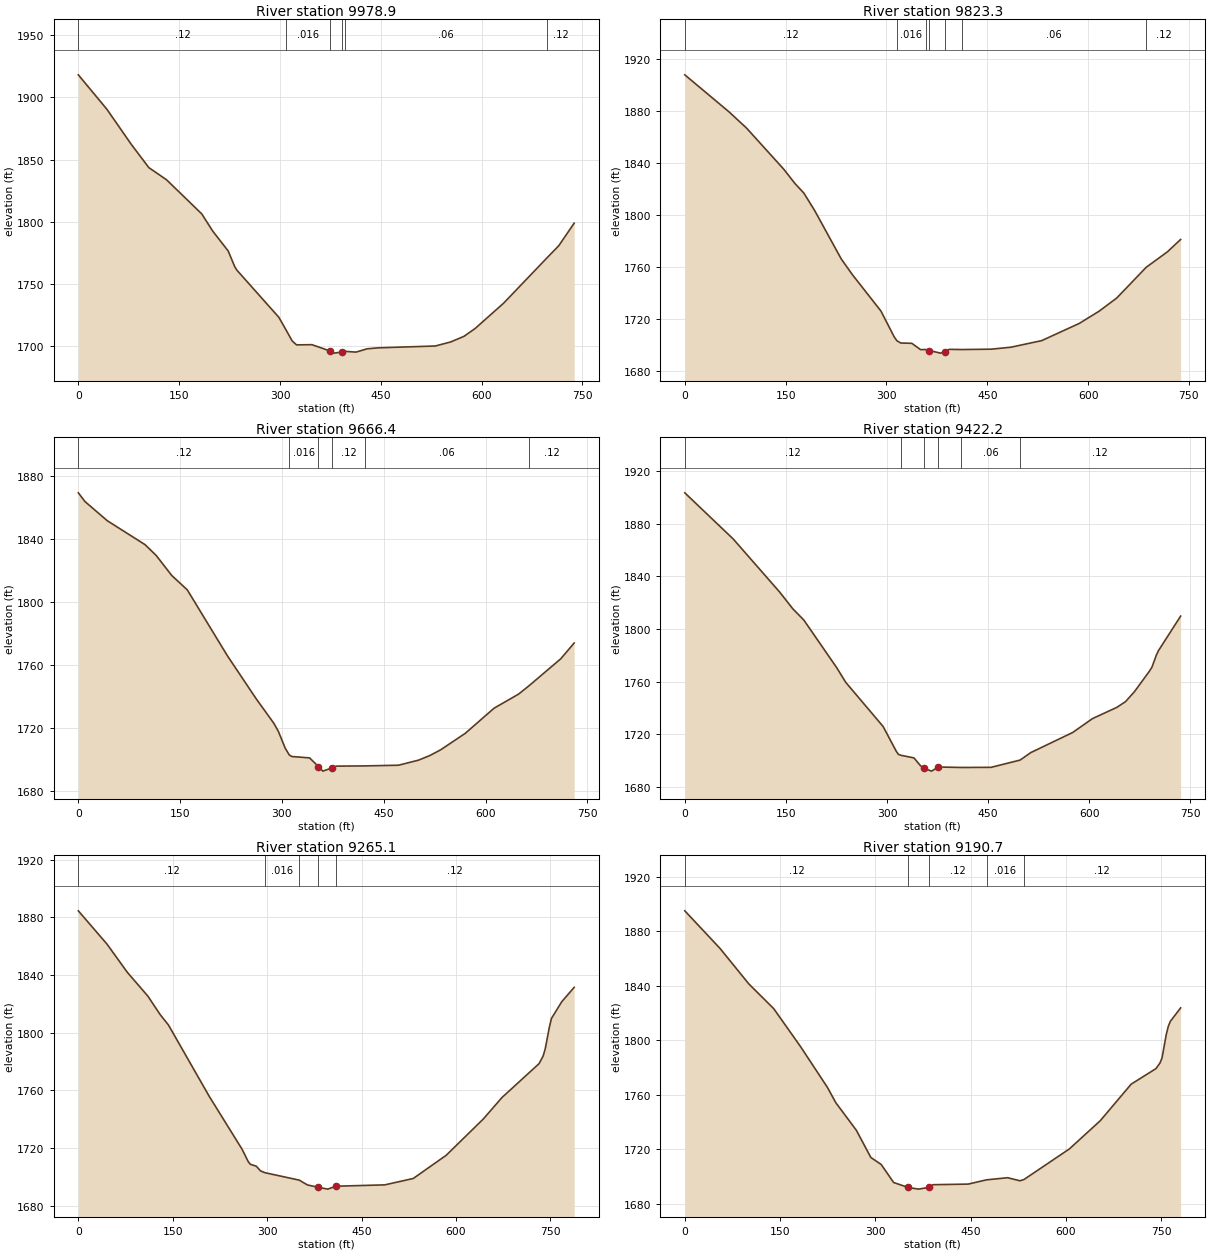
Type RM Length L Ch R = 1 ,9978.9  ,156,155.6,154.6
XS GIS Cut Line= 2
     2074542.226      199941.019     2074093.936       200526.79
#Sta/Elev= 30
       0    1918    42.6 1890.28    78.7 1862.24   104.9 1843.49   131.1 1833.79
   183.6 1806.36     200 1792.49   222.9 1776.61   232.8 1763.82     236  1761.1
   298.3 1723.31  309.611712.597     318 1704.43   324.6 1701.17   347.5 1701.34
   373.7 1696.43   380.3 1694.55   392.5 1695.46  396.821695.997   413.1 1695.36
   429.5 1698.01   445.8 1698.79   531.1 1700.28     554 1703.54   573.7 1708.04
   590.1 1714.24   632.7 1734.67  696.871770.869   714.7 1780.78   737.6 1798.89
#Mann= 6 ,-1 , 0
       0     .12       0  309.61    .016       0   373.7    .045       0
   392.5     .12       0  396.82     .06       0  696.87     .12       0
Bank Sta=373.7,392.5
XS Rating Curve= 0 ,0
Exp/Cntr=0.3,0.1

Type RM Length L Ch R = 1 ,9823.3  ,155.1,156.9,157.9
XS GIS Cut Line= 2
     2074420.698      199849.005     2073972.408      200434.776
#Sta/Elev= 30
       0 1907.72    65.6 1879.31    91.8 1866.78   147.5 1834.92   163.9 1824.04
     177  1816.8   193.4 1803.09   232.8 1765.96   249.2    1754   291.8 1725.91
   311.4 1706.16  315.451703.087   321.3 1701.32   337.7 1701.08   350.8 1696.21
  358.321696.294   363.9 1695.54   380.3 1693.53   386.8 1694.72   393.4 1696.44
  412.981696.298   455.7 1696.57   485.2 1698.08   531.1 1703.18   586.8 1716.39
   616.3 1725.79   642.6 1735.96  686.381759.579     718 1771.52   737.6 1781.02
#Mann= 7 ,-1 , 0
       0     .12       0  315.45    .016       0  358.32     .12       0
   363.9    .045       0   386.8     .12       0  412.98     .06       0
  686.38     .12       0
Bank Sta=363.9,386.8
XS Rating Curve= 0 ,0
Exp/Cntr=0.3,0.1

Type RM Length L Ch R = 1 ,9666.4  ,240.2,244.2,247.7
XS GIS Cut Line= 2
     2074315.736      199753.036     2073855.815      200320.543
#Sta/Elev= 30
       0 1869.17     9.8 1863.64    42.6  1851.5    98.3  1836.3   114.6 1829.51
   137.6 1816.76   160.5 1807.64   219.5  1765.9     262 1738.56   288.3 1722.83
   294.8 1717.79   304.6 1707.39  310.691702.937   314.5 1701.91   340.7 1701.04
   353.8 1695.54   360.3 1692.64   373.9  1694.7     380 1695.81  421.821695.945
   471.7 1696.39   501.2 1699.59   517.6 1702.47   533.9 1706.18     570 1716.59
   612.6 1732.58   648.6 1741.48   663.71746.686   710.8 1763.91   730.5 1773.92
#Mann= 6 ,-1 , 0
       0     .12       0  310.69    .016       0   353.8    .045       0
   373.9     .12       0  421.82     .06       0   663.7     .12       0
Bank Sta=353.8,373.9
XS Rating Curve= 0 ,0
Exp/Cntr=0.3,0.1

Type RM Length L Ch R = 1 ,9422.2  ,102.6,157.1,178.4
XS GIS Cut Line= 2
     2074207.831       199610.35     2073656.193      200097.005
#Sta/Elev= 30
       0 1903.53    71.9 1868.43   140.6 1828.22   160.2 1815.45   176.6 1806.89
   225.6 1770.52   238.7  1759.6   294.2 1726.03   313.9 1707.04   317.1 1704.76
   321.31704.058     340 1702.16   349.8 1696.13     355  1694.2   366.2  1692.1
     376 1695.23  410.431694.883   454.4 1694.98  497.461700.495   513.3 1706.18
   575.4 1721.43   604.8 1731.99   640.8  1740.5   653.9  1744.9     667  1752.4
   689.8 1768.37   693.1 1771.15   699.7 1780.37   702.9 1783.76   735.6 1809.86
#Mann= 6 ,-1 , 0
       0     .12       0   321.3    .016       0     355    .045       0
     376     .12       0  410.43     .06       0  497.46     .12       0
Bank Sta=355,376
XS Rating Curve= 0 ,0
Exp/Cntr=0.3,0.1

Type RM Length L Ch R = 1 ,9265.1  ,108.8,74.4,70.6
XS GIS Cut Line= 4
     2074150.108      199584.467     2073905.027      199772.575
     2073684.974       199719.19     2073526.844      199916.065
#Sta/Elev= 30
       0 1884.48    45.5 1861.43      78 1841.75   110.6 1825.28   130.1 1812.45
   143.1 1805.37   208.1 1755.74   260.2 1719.12   269.9  1710.6   273.2  1708.7
   282.9 1707.31   289.4 1704.14  296.311702.859  351.12 1697.67   363.9 1694.37
   380.1 1692.83   396.3 1691.44   409.2 1693.46   486.9 1694.39   532.2 1698.82
   584.6 1714.92   643.6 1740.11   673.1 1754.94   732.2 1778.51   738.7 1783.86
     742 1788.88   748.6 1803.95   751.8  1809.8   768.2 1821.45   787.9 1831.39
#Mann= 5 ,-1 , 0
       0     .12       0  296.31    .016       0  351.12     .12       0
   380.1    .045       0   409.2     .12       0
Bank Sta=380.1,409.2
XS Rating Curve= 0 ,0
Exp/Cntr=0.3,0.1

Type RM Length L Ch R = 1 ,9190.7  ,222.1,202.9,176.9
XS GIS Cut Line= 4
     2074134.483       199502.87     2073891.427      199683.426
     2073692.787      199671.013     2073526.844      199895.231
#Sta/Elev= 30
       0 1895.17    55.4 1867.59   100.9 1841.44     140 1823.32   182.3 1795.39
   224.6 1765.45   237.7 1754.27   270.2  1733.9     293 1713.93   309.3 1708.78
   328.9 1695.54   351.7 1691.92     368 1690.68   384.4 1691.96   390.9 1693.93
   446.3 1694.38  475.251697.511   508.3 1699.06   527.8 1696.82  534.131697.737
   605.6 1720.22   654.3 1740.97   702.9  1767.8   741.8 1779.19   748.3 1783.33
   751.6 1787.23     758 1803.88   761.3 1810.13   764.5  1813.9   780.8 1823.84
#Mann= 5 ,-1 , 0
       0     .12       0   351.7    .045       0   384.4     .12       0
  475.25    .016       0  534.13     .12       0
Bank Sta=351.7,384.4
XS Rating Curve= 0 ,0
Exp/Cntr=0.3,0.1

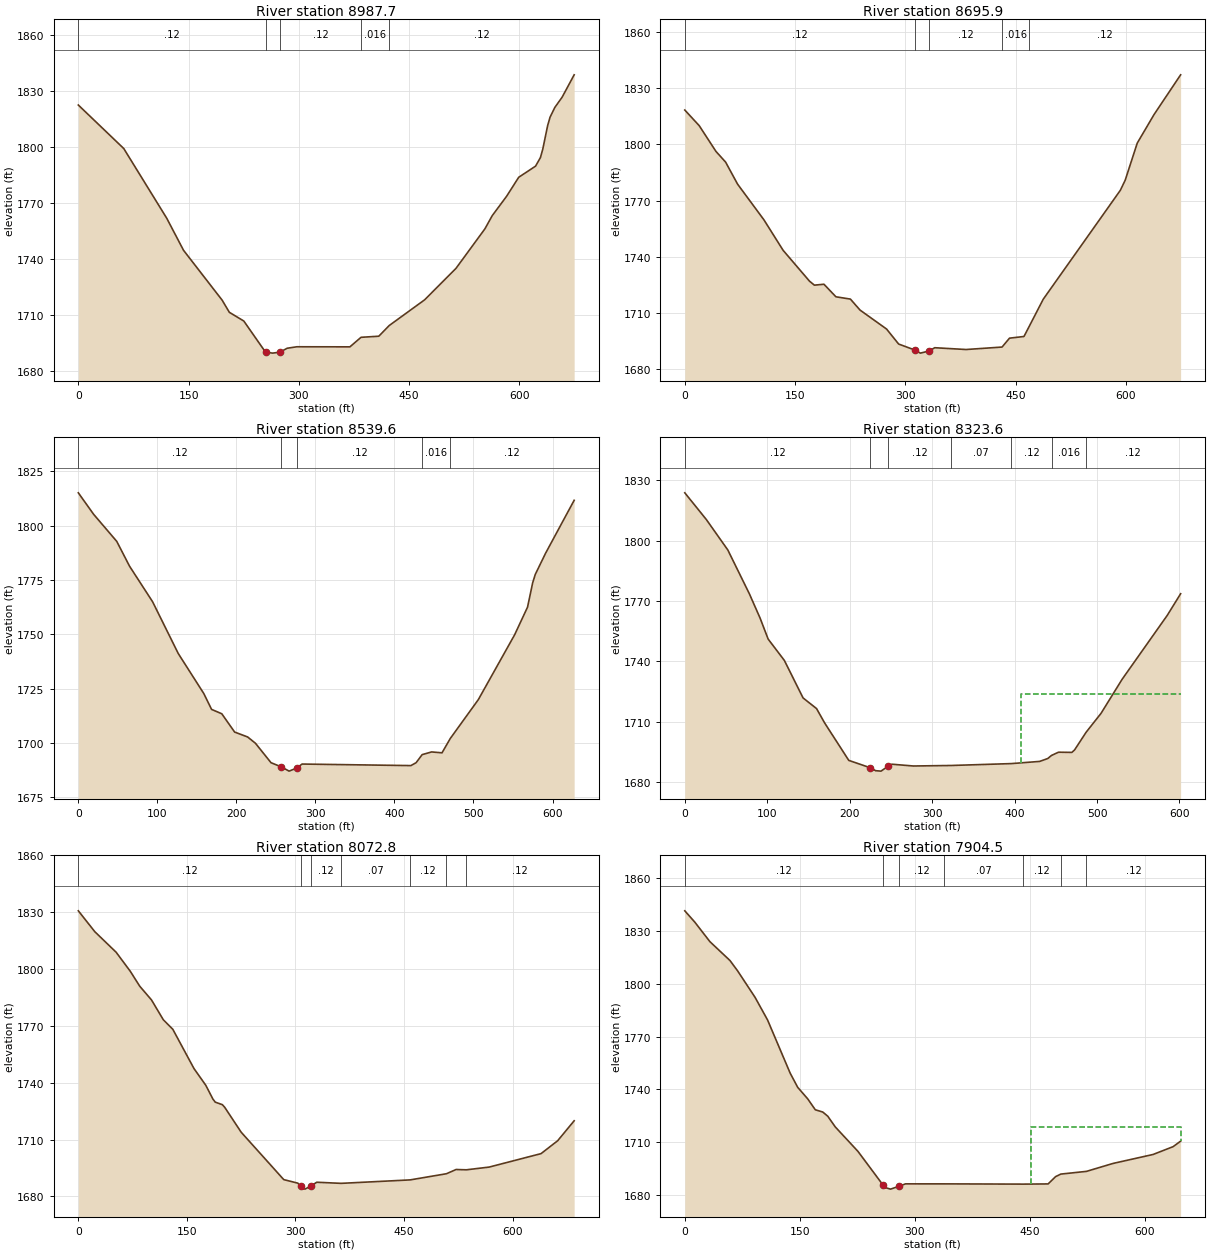
Type RM Length L Ch R = 1 ,8987.7  ,297.9,291.8,286.3
XS GIS Cut Line= 3
     2073867.006      199333.165     2073785.524      199450.787
     2073491.481      199893.289
#Sta/Elev= 30
       0 1822.46    61.8 1799.18   120.3 1761.85   143.1 1744.72   195.6 1718.04
   205.4 1711.54   225.1 1706.86   254.6 1690.21   264.4 1689.69   274.3 1690.24
   284.1 1692.31   297.2 1693.09   369.4 1693.05   384.51698.152   408.7 1698.74
  422.871704.463     471 1718.21   513.7 1735.07     553  1756.2   562.9 1763.22
   582.6 1773.68     599  1783.8   621.9 1789.76   628.5 1794.33   631.7 1798.81
   638.3  1811.4   641.6 1815.93   648.1 1821.17     658 1826.63   674.4 1838.63
#Mann= 5 ,-1 , 0
       0     .12       0   254.6    .045       0   274.3     .12       0
   384.5    .016       0  422.87     .12       0
Bank Sta=254.6,274.3
XS Rating Curve= 0 ,0
Exp/Cntr=0.3,0.1

Type RM Length L Ch R = 1 ,8695.9  ,160.8,156.3,150.5
XS GIS Cut Line= 3
     2073627.422      199208.165     2073495.594      199374.398
     2073387.955      199824.051
#Sta/Elev= 30
       0 1818.38    19.6 1810.03    42.4 1796.25    55.5 1790.55    71.8 1778.76
   107.7 1759.64   133.8 1743.33   169.7 1726.85   176.3 1724.73   189.3 1725.22
   205.6 1718.51   225.3 1717.27   238.4  1711.4   274.5 1701.26   290.9 1693.24
   313.8 1689.91   320.4 1688.38   332.3  1689.5     340 1691.27   382.7 1690.31
  431.59 1691.63   441.7 1696.38   461.4 1697.28  468.741702.842   487.6  1717.2
   592.5 1775.46   599.1 1780.86   615.5  1800.7   638.4    1816   674.5 1837.21
#Mann= 5 ,-1 , 0
       0     .12       0   313.8    .045       0   332.3     .12       0
  431.59    .016       0  468.74     .12       0
Bank Sta=313.8,332.3
XS Rating Curve= 0 ,0
Exp/Cntr=0.3,0.1

Type RM Length L Ch R = 1 ,8539.6  ,214.4,216,217
XS GIS Cut Line= 3
     2073346.288      199146.967     2073332.399      199334.467
     2073321.983      199773.704
#Sta/Elev= 30
       0 1815.15    19.4 1805.24    48.6  1792.8    64.8 1781.36      94 1764.96
   126.4 1741.16   158.8 1722.67   168.6  1715.4   181.5 1713.39   197.8 1704.95
   214.2  1702.7   224.1  1699.8   243.8 1690.85   256.9 1688.91   266.7 1686.96
   276.5 1688.39   283.1 1690.22   420.8 1689.51   427.4 1690.84  435.071694.556
     447  1695.8   460.2 1695.39  470.571701.952   506.1 1719.87     552 1749.71
   568.4 1762.48   574.9  1773.7   578.2 1777.56   591.3 1787.37   627.4  1811.7
#Mann= 5 ,-1 , 0
       0     .12       0   256.9    .045       0   276.5     .12       0
  435.07    .016       0  470.57     .12       0
Bank Sta=256.9,276.5
XS Rating Curve= 0 ,0
Exp/Cntr=0.3,0.1

Type RM Length L Ch R = 1 ,8323.6  ,251.3,250.8,248.8
XS GIS Cut Line= 3
     2073141.427       199150.44     2073110.177      199615.717
     2073115.112      199750.661
#Sta/Elev= 30
       0 1823.81    26.1 1810.55    52.2  1795.4    78.3 1773.64    91.3 1761.57
   101.1 1751.11   120.7 1740.54   143.5 1721.84   159.8 1716.58   169.6 1709.44
   198.9 1690.82     225 1687.15   231.4  1685.7     238 1685.48   246.4 1687.85
   251.1 1688.92   277.2 1688.03  322.931688.281  396.161689.224   430.4 1690.31
   440.2 1691.73  444.811693.282   453.3 1694.88   469.5 1694.79   472.8 1696.03
  486.671704.748   504.9 1714.22   530.6 1731.22   585.3 1762.97   601.4 1773.65
#Mann= 7 ,-1 , 0
       0     .12       0     225    .045       0   246.4     .12       0
  322.93     .07       0  396.16     .12       0  444.81    .016       0
  486.67     .12       0
#XS Ineff= 2 , 0
                          407.57         1723.81
Permanent Ineff=
       F       F
Bank Sta=225,246.4
XS Rating Curve= 0 ,0
Exp/Cntr=0.3,0.1

Type RM Length L Ch R = 1 ,8072.8  ,163.2,168.3,173.3
XS GIS Cut Line= 3
     2072844.552      199098.356     2072900.108       199346.62
     2072893.163      199777.176
#Sta/Elev= 30
       0 1830.77    22.8 1819.74    52.2 1808.92    71.8 1798.85    84.8 1790.99
   101.1 1783.71   117.4 1773.27   130.5 1768.25   159.8 1747.48   176.1 1738.66
   185.9 1731.41   189.2 1729.75     199 1728.43   202.2 1727.06     225 1713.88
   283.8 1688.86   303.3 1686.99     307 1685.33   313.1 1683.84     322 1685.65
   329.4 1687.48   363.11686.888  458.321688.707  508.571691.966   521.9  1694.2
  536.041694.037   567.6 1695.48   639.3 1702.59   662.2 1709.38     685 1719.92
#Mann= 7 ,-1 , 0
       0     .12       0     307    .045       0     322     .12       0
   363.1     .07       0  458.32     .12       0  508.57    .016       0
  536.04     .12       0
Bank Sta=307,322
XS Rating Curve= 0 ,0
Exp/Cntr=0.3,0.1

Type RM Length L Ch R = 1 ,7904.5  ,342.2,347.1,346.6
XS GIS Cut Line= 3
     2072799.297      199111.811     2072741.869      199377.433
      2072638.95      199738.307
#Sta/Elev= 30
       0 1841.55    13.1  1835.1    32.7 1824.04    58.9 1813.29    68.8 1807.46
    91.7 1792.31     108 1779.44   137.5 1749.17   147.3 1741.12   160.4 1734.53
   170.3 1728.33   180.1 1727.02   186.6 1724.63   196.4 1718.54   225.9 1704.68
   258.7 1685.46   261.9 1683.99   268.5 1683.16   279.3 1684.77   288.1 1686.16
  338.491686.154  441.52 1686.01   474.1 1686.12   483.9 1690.28  490.691691.719
  524.121693.265   558.9 1697.79   611.1 1702.89   637.2 1707.33     647 1710.47
#Mann= 7 ,-1 , 0
       0     .12       0   258.7    .045       0   279.3     .12       0
  338.49     .07       0  441.52     .12       0  490.69    .016       0
  524.12     .12       0
#XS Ineff= 2 , 0
                          451.89         1718.79
Permanent Ineff=
       F       F
Bank Sta=258.7,279.3
XS Rating Curve= 0 ,0
Exp/Cntr=0.3,0.1

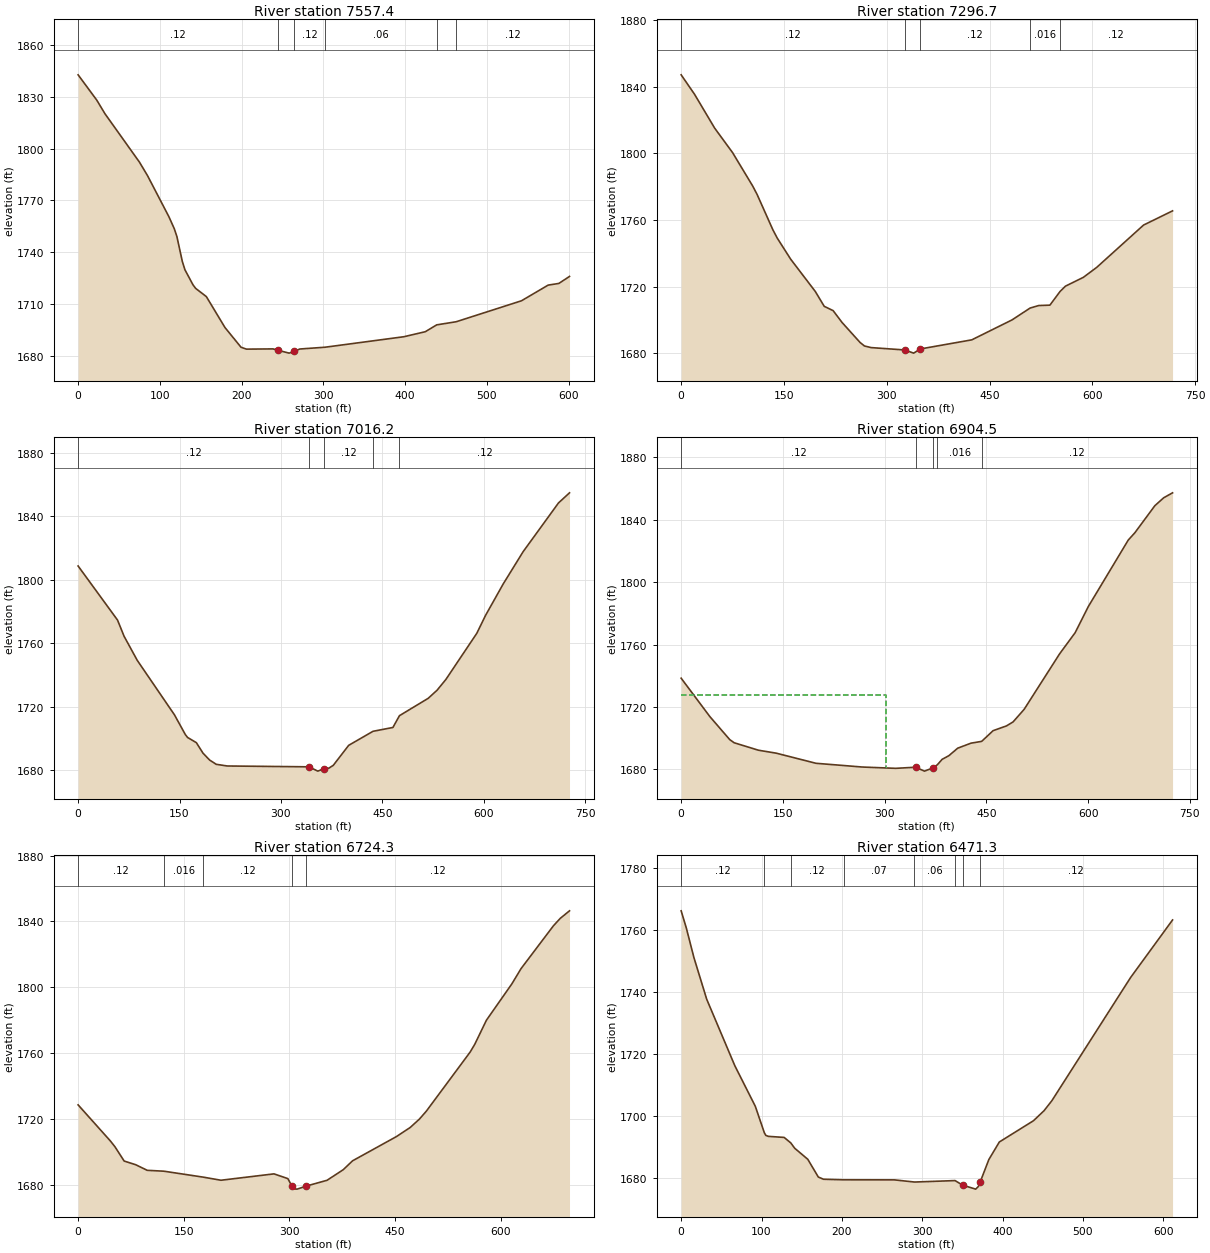
Type RM Length L Ch R = 1 ,7557.4  ,251,260.6,268
XS GIS Cut Line= 2
     2072489.402      199106.603     2072315.038       199681.69
#Sta/Elev= 30
       0 1842.59    22.9 1827.92    32.7 1820.21    75.1 1792.08    84.9 1784.33
     111 1760.63   117.6 1753.68   120.8 1749.16   127.4 1734.83   130.6 1729.99
   140.4 1721.32   143.7 1719.22   156.8 1714.46   179.6 1696.58   199.2  1685.2
   205.8  1684.1   238.4 1684.23     245 1683.37     258 1681.79     264 1682.76
   271.1 1684.17  302.061685.204   398.4 1691.27   424.6 1694.17  438.491698.122
  462.311699.919   542.2 1712.04   574.8 1721.09   587.9 1722.06   600.9 1726.11
#Mann= 6 ,-1 , 0
       0     .12       0     245    .045       0     264     .12       0
  302.06     .06       0  438.49    .016       0  462.31     .12       0
Bank Sta=245,264
XS Rating Curve= 0 ,0
Exp/Cntr=0.3,0.1

Type RM Length L Ch R = 1 ,7296.7  ,273.5,280.6,279.2
XS GIS Cut Line= 3
     2072389.691      199030.648     2072124.066       199377.87
     2071927.885      199577.523
#Sta/Elev= 30
       0 1847.23    19.6 1835.51    48.9 1815.23      75 1800.54   104.4 1780.46
   110.9 1775.35   133.8 1754.22   140.3 1749.14   159.9 1736.49   195.8 1717.11
   208.8 1708.21   221.8 1705.62   234.9 1698.48     261 1686.55   267.5  1684.4
   277.3 1683.43   326.2 1682.01   339.3 1680.11   349.1 1682.62   424.1 1688.08
   482.7 1700.02  509.171707.159   521.8 1708.69   538.1 1708.92  552.981717.148
   560.8 1720.32   586.9 1725.61   606.4 1731.59   674.8 1757.01   717.1 1765.54
#Mann= 5 ,-1 , 0
       0     .12       0   326.2    .045       0   349.1     .12       0
  509.17    .016       0  552.98     .12       0
Bank Sta=326.2,349.1
XS Rating Curve= 0 ,0
Exp/Cntr=0.3,0.1

Type RM Length L Ch R = 1 ,7016.2  ,140.5,111.7,113.3
XS GIS Cut Line= 3
     2072255.027      198955.561     2072111.797      199044.103
     2071699.731         199421.
#Sta/Elev= 30
       0 1808.77    58.3 1774.68      68 1764.48    87.4 1749.34   142.5 1714.94
   158.7 1702.42   161.9 1700.68   174.9 1697.38   184.7 1690.78   194.5 1686.43
   204.3 1683.74   220.6 1682.68   341.5 1682.15   354.5 1679.44   364.3 1681.02
   370.9 1681.32   377.4 1683.09   400.2  1695.7  436.181704.547   465.6 1706.96
  475.291714.396   517.8 1725.34   530.9 1730.44   543.9  1737.2   589.7 1766.35
   602.7 1777.68   628.8 1797.49   658.2 1817.79   710.5 1848.52   726.8  1854.9
#Mann= 5 ,-1 , 0
       0     .12       0   341.5    .045       0   364.3     .12       0
  436.18    .016       0  475.29     .12       0
Bank Sta=341.5,364.3
XS Rating Curve= 0 ,0
Exp/Cntr=0.3,0.1

Type RM Length L Ch R = 1 ,6904.5  ,148.4,180.2,180.2
XS GIS Cut Line= 4
      2071997.33      198737.245     2071936.566      198919.537
     2071907.304      199083.478     2071622.887      199313.442
#Sta/Elev= 30
       0 1738.43    42.3 1713.82    71.6 1699.05    78.2 1697.02     114 1692.24
     140 1690.37   198.7 1683.87   267.3 1681.46   316.2 1680.63   345.6 1681.34
   358.7 1678.84   371.8 1680.99  377.821682.986   384.8 1686.43   394.6 1688.72
   407.7 1693.56   427.3 1696.77  443.01 1697.92   459.9 1704.79   479.5 1707.82
   489.3 1710.39   505.6 1718.44   557.9 1754.04   580.8 1767.59   600.3 1784.42
   659.1 1826.99   668.9 1831.71   698.3 1849.02   711.4 1854.12   724.4 1857.28
#Mann= 5 ,-1 , 0
       0     .12       0   345.6    .045       0   371.8     .12       0
  377.82    .016       0  443.01     .12       0
#XS Ineff= 2 , 0
          302.09 1727.38
Permanent Ineff=
       F       F
Bank Sta=345.6,371.8
XS Rating Curve= 0 ,0
Exp/Cntr=0.3,0.1

Type RM Length L Ch R = 1 ,6724.3  ,256.1,253,248.6
XS GIS Cut Line= 3
      2071934.83      198686.898     2071856.705      198916.065
     2071489.161      199185.655
#Sta/Elev= 30
       0 1728.49    45.8 1706.58    52.4    1703    65.4 1694.36    81.8 1692.13
    98.2 1688.72  121.871688.191  177.831684.574   202.9  1682.7   278.2 1686.57
   297.9 1683.69   303.3  1679.4   307.7 1677.42     311  1677.3   324.1 1679.16
   353.6 1682.68   376.6 1689.12   389.7 1694.48     452  1709.2   471.7 1714.77
   484.8 1719.88   494.6 1724.69   556.9 1760.64   563.5 1765.43   579.9 1779.93
     616 1801.99   629.1 1811.29     675 1837.26   684.8 1841.83   697.9 1846.39
#Mann= 5 ,-1 , 0
       0     .12       0  121.87    .016       0  177.83     .12       0
   303.3    .045       0   324.1     .12       0
Bank Sta=303.3,324.1
XS Rating Curve= 0 ,0
Exp/Cntr=0.3,0.1

Type RM Length L Ch R = 1 ,6471.3  ,386.1,385.2,382.4
XS GIS Cut Line= 3
     2071898.256      198564.936     2071811.566       198596.62
     2071445.246      198964.676
#Sta/Elev= 30
       0  1766.3     6.4 1760.78    15.9  1751.2    31.8 1737.75    66.8 1716.28
    92.3 1703.17  103.491694.661   105.4 1693.77   108.6 1693.46   128.2 1693.12
  136.511691.329   141.3 1689.63   157.6 1686.06   170.7 1680.33   177.2 1679.61
  202.121679.434   265.4 1679.41  290.41 1678.71  340.921679.178   350.3 1677.71
   366.6 1676.42   369.9 1677.27  371.96 1678.57     383 1685.99     396 1691.64
   438.5 1698.51   451.6 1701.73   461.4 1704.98   559.3 1744.73   611.6 1763.35
#Mann= 8 ,-1 , 0
       0     .12       0  103.49    .016       0  136.51     .12       0
  202.12     .07       0  290.41     .06       0  340.92     .12       0
   350.3    .045       0  371.96     .12       0
Bank Sta=350.3,371.96
XS Rating Curve= 0 ,0
Exp/Cntr=0.3,0.1

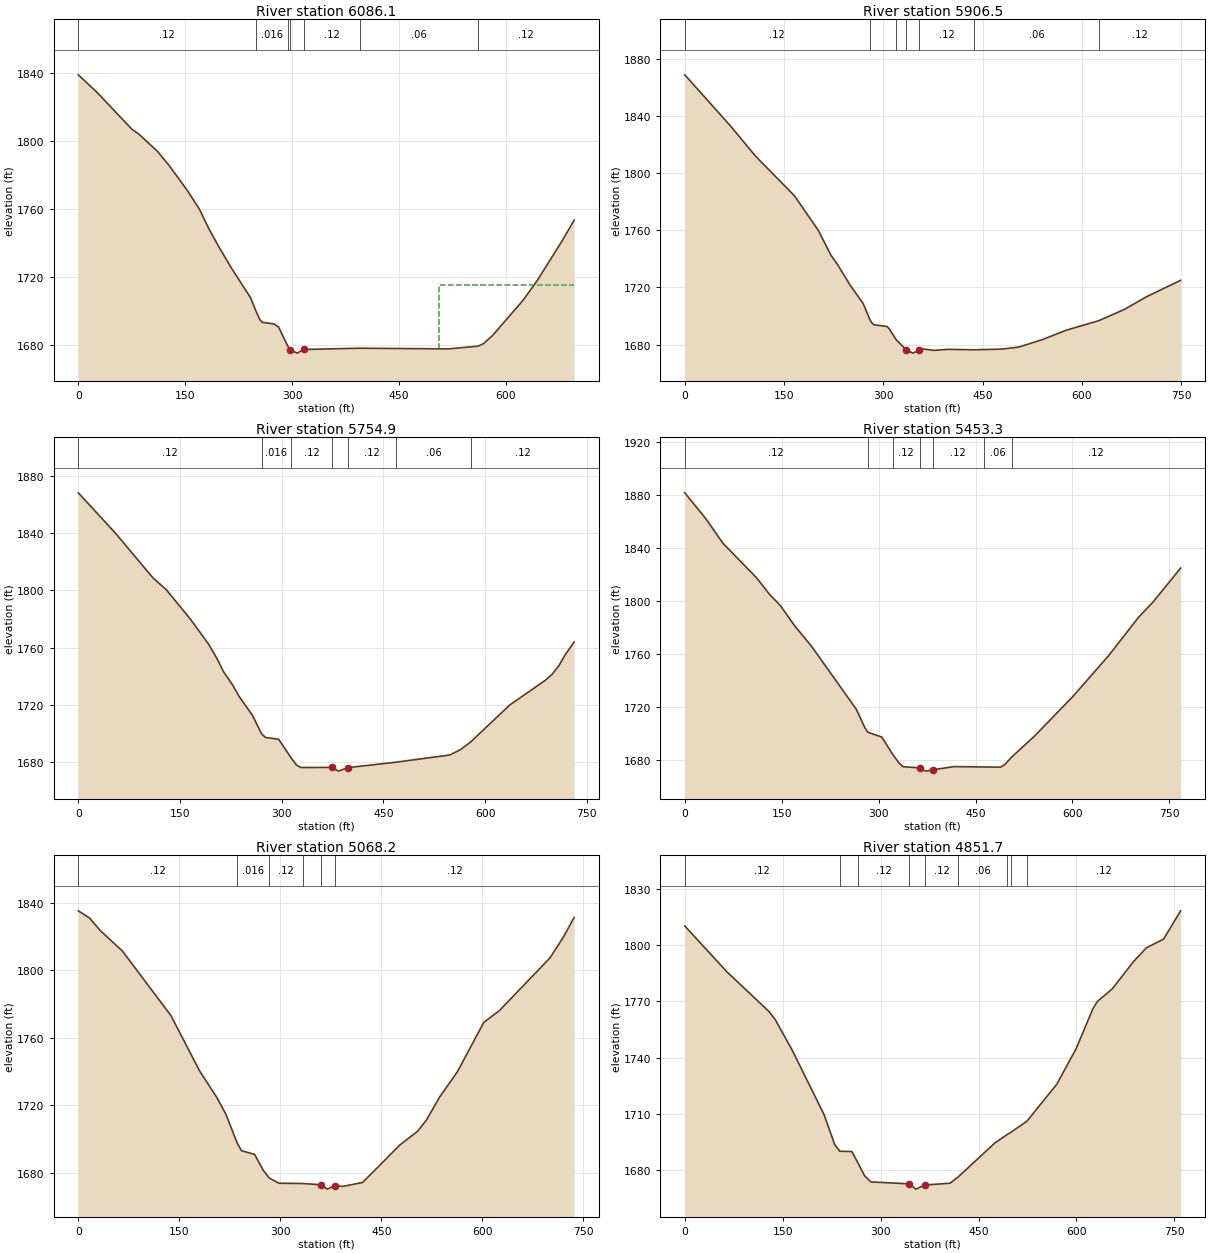
Type RM Length L Ch R = 1 ,6086.1  ,178,179.6,181.9
XS GIS Cut Line= 2
     2071808.094      198214.676     2071354.969      198742.454
#Sta/Elev= 30
       0 1838.68    26.1 1828.42    75.1 1806.72    84.9 1803.82     111  1793.7
   127.4 1785.35   153.5 1770.33   169.8 1759.74   182.9 1748.38     196 1738.36
   215.5 1724.55   241.7  1707.6  249.571699.369   254.7 1694.71     258 1693.14
   274.3  1692.2   280.9 1690.38  294.051678.961   297.2 1677.08     307 1675.02
   316.5 1677.16   394.51677.919   519.3 1677.51  560.731679.111   568.2 1680.55
   581.3 1685.45   623.8 1706.05   643.4 1717.46   679.3 1741.42   695.6 1753.23
#Mann= 7 ,-1 , 0
       0     .12       0  249.57    .016       0  294.05     .12       0
   297.2    .045       0   316.5     .12       0   394.5     .06       0
  560.73     .12       0
#XS Ineff= 2 , 0
                          506.11         1715.07
Permanent Ineff=
       F       F
Bank Sta=297.2,316.5
XS Rating Curve= 0 ,0
Exp/Cntr=0.3,0.1

Type RM Length L Ch R = 1 ,5906.5  ,149.7,151.6,150.9
XS GIS Cut Line= 3
     2071695.246      198074.051     2071490.385      198313.634
     2071188.614      198625.671
#Sta/Elev= 30
       0 1868.69    68.2 1833.39   107.2 1811.66   165.7 1784.09   201.5  1760.1
     221 1742.43   230.7 1736.05   250.2 1721.36   269.7 1708.61  279.251697.896
   282.7 1695.14     286 1693.82   305.5 1692.69   308.7 1691.19  319.921683.117
   334.8  1676.3   344.6 1674.02   354.4 1676.05   360.9 1676.88   377.2 1675.92
   396.8 1676.67  436.691676.356   478.4 1676.81   504.5 1678.23   540.4 1683.48
   576.3 1690.03  625.791696.751   664.5 1704.64   697.1 1713.31   749.3 1724.95
#Mann= 7 ,-1 , 0
       0     .12       0  279.25    .016       0  319.92     .12       0
   334.8    .045       0   354.4     .12       0  436.69     .06       0
  625.79     .12       0
Bank Sta=334.8,354.4
XS Rating Curve= 0 ,0
Exp/Cntr=0.3,0.1

Type RM Length L Ch R = 1 ,5754.9  ,297.5,301.6,300
XS GIS Cut Line= 3
     2071594.552       197994.19     2071401.844      198218.148
     2071087.608      198520.231
#Sta/Elev= 30
       0 1868.05    55.2 1839.63   110.4 1808.47   129.9 1800.31   165.6 1779.62
   191.6 1762.71   204.6 1752.22   214.3 1742.98   227.3 1734.01     237 1725.94
   256.5 1712.84  270.451699.642     276 1697.18   295.5  1695.9  313.561683.103
   321.7 1677.94   328.2  1676.2   374.1 1676.24   383.9 1673.65     397 1676.05
  469.221679.931   547.8 1684.93   564.2 1688.82   578.81694.072   636.3 1719.85
   688.7 1737.06   698.6 1741.21   708.4 1747.03   718.2 1755.04   731.3 1763.85
#Mann= 7 ,-1 , 0
       0     .12       0  270.45    .016       0  313.56     .12       0
   374.1    .045       0     397     .12       0  469.22     .06       0
   578.8     .12       0
Bank Sta=374.1,397
XS Rating Curve= 0 ,0
Exp/Cntr=0.3,0.1

Type RM Length L Ch R = 1 ,5453.3  ,377,385.1,384.6
XS GIS Cut Line= 2
     2071500.652       197866.95      2070901.74      198346.868
#Sta/Elev= 30
       0 1881.58    32.8 1861.99      59 1843.62   111.5 1817.37   131.2  1805.1
   147.6 1796.85   170.6 1781.12   196.8 1765.61   265.7 1718.43   278.8  1704.6
  283.281701.284     305 1697.59  321.721684.691   331.3 1678.34   337.8  1675.3
   364.1  1674.4   367.3 1672.88   373.9 1671.97   383.7 1672.92   416.5 1675.39
  462.911675.112   488.7 1674.97   495.2 1676.85  505.831682.489   541.2 1698.31
   600.2 1727.92     656 1758.91   701.9 1787.58   724.8 1799.33   767.5 1824.89
#Mann= 7 ,-1 , 0
       0     .12       0  283.28    .016       0  321.72     .12       0
   364.1    .045       0   383.7     .12       0  462.91     .06       0
  505.83     .12       0
Bank Sta=364.1,383.7
XS Rating Curve= 0 ,0
Exp/Cntr=0.3,0.1

Type RM Length L Ch R = 1 ,5068.2  ,213.1,216.5,215.9
XS GIS Cut Line= 2
     2071304.621      197688.634     2070735.177      198155.648
#Sta/Elev= 30
       0 1835.15    16.4 1830.98    32.7 1823.42    65.5 1811.34   137.5 1773.19
     180 1740.48   206.2 1724.39   219.3 1714.64   235.8 1697.91   242.2 1693.21
   261.8 1690.99   274.9 1681.47  283.59 1677.01   297.9 1673.92  333.631673.759
     360 1673.02   369.9 1670.43   380.9 1672.54   392.8 1672.04   422.2 1674.36
   477.9 1696.67   504.1 1704.71   517.2 1711.43   536.8 1724.99     563 1739.87
   602.3 1769.14   625.2    1776   700.4 1807.22   720.1 1819.31   736.5 1831.27
#Mann= 6 ,-1 , 0
       0     .12       0   235.8    .016       0  283.59     .12       0
  333.63     .06       0     360    .045       0   380.9     .12       0
Bank Sta=360,380.9
XS Rating Curve= 0 ,0
Exp/Cntr=0.3,0.1

Type RM Length L Ch R = 1 ,4851.7  ,196,190.3,184.5
XS GIS Cut Line= 3
      2071247.33      197633.079     2071067.527      197671.707
     2070613.193      198025.232
#Sta/Elev= 30
       0 1810.15    64.5 1785.73   129.1 1764.55   138.7  1760.2   164.6 1743.97
   213.3 1709.71   229.7 1693.69  237.371690.162   255.9 1690.02  265.151684.052
   275.5 1677.04   285.3 1673.83   344.2  1672.8     354 1669.99   367.6 1672.18
   406.3 1673.14  418.631676.428     475 1694.57  494.351699.168  499.051700.103
  524.151706.188   569.9 1725.87   599.3 1744.64   625.5 1766.27     632 1769.92
   654.9 1776.65   687.6 1791.25   707.2 1798.52   733.4 1803.12   759.6 1818.21
#Mann= 9 ,-1 , 0
       0     .12       0  237.37    .016       0  265.15     .12       0
   344.2    .045       0   367.6     .12       0  418.63     .06       0
  494.35     .12       0  499.05     .06       0  524.15     .12       0
Bank Sta=344.2,367.6
XS Rating Curve= 0 ,0
Exp/Cntr=0.3,0.1

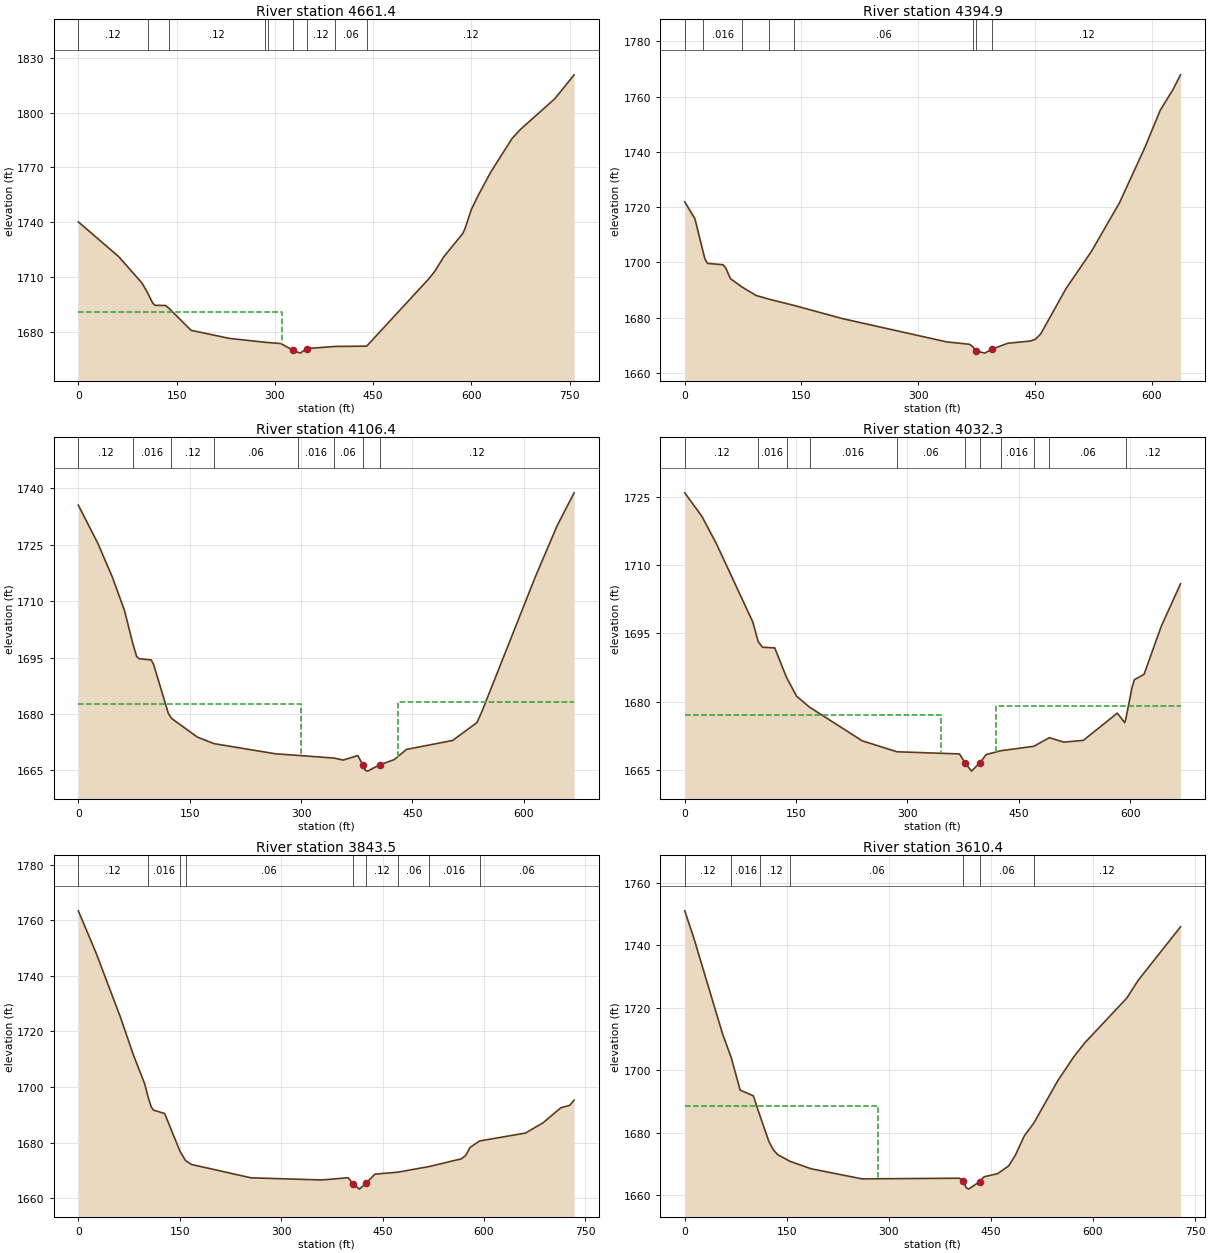
Type RM Length L Ch R = 1 ,4661.4  ,256.2,266.5,271
XS GIS Cut Line= 3
      2071099.76      197490.717     2070913.996      197521.967
     2070570.233      197974.508
#Sta/Elev= 30
       0 1740.15    61.7 1721.07    97.4 1706.53  105.751701.213   113.7 1695.54
   116.9 1694.44   133.2 1694.32   138.81692.643   172.1 1680.72   230.8 1676.29
   285.61674.159  289.531674.062   309.2 1673.46   327.6 1669.82   338.6 1668.23
   348.4 1670.74  392.471671.901  440.111672.064   534.6 1708.82   544.4 1713.21
   557.4 1720.82   586.8 1733.78   590.1 1736.36   599.9 1746.98   609.7  1754.2
   629.3  1767.3     662  1785.8     675 1790.87   727.3  1807.6   756.7 1820.69
#Mann= 9 ,-1 , 0
       0     .12       0  105.75    .016       0   138.8     .12       0
   285.6     .06       0  289.53     .12       0   327.6    .045       0
   348.4     .12       0  392.47     .06       0  440.11     .12       0
#XS Ineff= 2 , 0
          311.14 1690.86
Permanent Ineff=
       F       F
Bank Sta=327.6,348.4
XS Rating Curve= 0 ,0
Exp/Cntr=0.3,0.1

Type RM Length L Ch R = 1 ,4394.9  ,289.8,288.5,285.3
XS GIS Cut Line= 2
     2070939.098      197280.923     2070445.246      197683.426
#Sta/Elev= 30
       0 1721.92    13.1  1715.8   24.091703.294    26.1 1701.14    29.4 1699.64
      49 1699.16    52.3 1698.18    58.8 1694.09   74.151691.001    91.5 1688.06
   108.71686.666  140.891684.397   202.6 1679.66   336.5 1671.23   365.9 1670.36
     3701669.556   374.4 1667.93   385.5 1667.16   395.3 1668.65   414.9 1670.72
   444.3 1671.55   450.9 1672.24   457.4 1674.09   490.1 1690.59   522.8 1704.07
   558.7 1721.61   591.4 1741.67     611 1755.06   627.3 1762.51   637.1  1767.9
#Mann= 8 ,-1 , 0
       0     .12       0   24.09    .016       0   74.15     .08       0
   108.7     .12       0  140.89     .06       0     370     .12       0
   374.4    .045       0   395.3     .12       0
Bank Sta=374.4,395.3
XS Rating Curve= 0 ,0
Exp/Cntr=0.3,0.1

Type RM Length L Ch R = 1 ,4106.4  ,71.5,74.1,75.5
XS GIS Cut Line= 3
     2070858.441      197054.954     2070681.358      197173.009
      2070341.08      197475.092
#Sta/Elev= 30
       0 1735.54    26.2 1725.42    45.8 1716.42    62.2 1707.52   73.211698.873
    78.6 1695.28    81.9 1694.69    98.2 1694.39   101.5 1693.12   121.2  1680.2
  125.351678.873   160.4 1673.86  182.71 1672.13   265.2 1669.44  296.36 1668.99
  343.921668.295   356.9 1667.77   376.5 1668.96     383 1666.54   386.3 1665.08
   389.6 1664.82     406  1666.5   425.6 1667.89     442 1670.59   504.2 1672.98
   536.9 1677.72   543.4 1680.55   615.5 1716.44   644.9 1730.05   667.8 1738.81
#Mann= 8 ,-1 , 0
       0     .12       0   73.21    .016       0  125.35     .12       0
  182.71     .06       0  296.36    .016       0  343.92     .06       0
     383    .045       0     406     .12       0
#XS Ineff= 2 , 0
          300.34 1682.57  430.13         1683.24
Permanent Ineff=
       F       F
Bank Sta=383,406
XS Rating Curve= 0 ,0
Exp/Cntr=0.3,0.1

Type RM Length L Ch R = 1 ,4032.3  ,185.8,188.8,191.8
XS GIS Cut Line= 3
      2070849.76      196985.509     2070672.677      197103.565
     2070332.399      197405.648
#Sta/Elev= 30
       0 1725.98    22.9 1720.85    42.6 1714.79    91.7 1697.52   98.951693.191
   104.8 1691.96   121.2 1691.82  137.111685.305   150.6 1681.19   168.21678.758
     239 1671.35  285.841668.935     370 1668.46   378.1 1666.38   386.3 1664.67
   397.5 1666.49     406 1668.32  425.731669.163  470.221670.141  491.191672.044
   510.7 1671.05   536.9 1671.45   582.7 1677.45   592.6 1675.35  594.141676.192
   602.4 1683.02   605.6 1684.81   618.7    1686   641.7 1696.51   667.8 1705.94
#Mann= 11 ,-1 , 0
       0     .12       0   98.95    .016       0  137.11     .12       0
   168.2    .016       0  285.84     .06       0   378.1    .045       0
   397.5     .12       0  425.73    .016       0  470.22     .12       0
  491.19     .06       0  594.14     .12       0
#XS Ineff= 2 , 0
          344.66 1677.08  419.45         1679.08
Permanent Ineff=
       F       F
Bank Sta=378.1,397.5
XS Rating Curve= 0 ,0
Exp/Cntr=0.3,0.1

Type RM Length L Ch R = 1 ,3843.5  ,231.6,233.1,234.5
XS GIS Cut Line= 2
     2070765.776      196823.599     2070178.937      197263.175
#Sta/Elev= 30
       0 1763.34    26.2 1748.23    62.2 1725.13    81.8 1711.27    98.2  1701.1
  103.441696.134     108 1692.69   111.3 1691.64   127.7 1690.42  150.481676.784
   158.61673.517   166.9 1672.14   255.3 1667.31   360.1 1666.54   399.3 1667.34
   405.9 1665.17   415.7 1663.24   425.5 1665.38   438.6 1668.62   472.91669.356
  518.621671.354   566.3 1674.12   572.8 1675.31   579.4 1678.24  593.38 1680.56
   661.2  1683.4   687.4 1687.12   713.6 1692.51   726.7 1693.38   733.2 1695.23
#Mann= 9 ,-1 , 0
       0     .12       0  103.44    .016       0  150.48     .12       0
   158.6     .06       0   405.9    .045       0   425.5     .12       0
   472.9     .06       0  518.62    .016       0  593.38     .06       0
Bank Sta=405.9,425.5
XS Rating Curve= 0 ,0
Exp/Cntr=0.3,0.1

Type RM Length L Ch R = 1 ,3610.4  ,208.2,206,203.7
XS GIS Cut Line= 3
     2070640.382       196664.97     2070333.925      196862.435
     2070029.347      197061.843
#Sta/Elev= 30
       0  1751.1      13 1742.64    55.3  1711.9   68.451704.032    81.4 1693.72
   100.9 1691.85   110.21685.696   123.7 1677.25   130.2 1674.58   136.7 1673.01
  155.121670.858   185.5 1668.52   260.4 1665.28   403.9 1665.48   409.5 1664.46
   413.8 1662.39     417 1661.99   433.4 1664.37     440 1665.95   459.7 1666.93
   476.1 1669.43   485.9 1672.86     499 1679.02  512.941683.126   548.2 1696.69
   571.2 1704.18   587.6 1708.76   649.9 1723.22   666.3 1728.83   728.6 1745.97
#Mann= 7 ,-1 , 0
       0     .12       0   68.45    .016       0   110.2     .12       0
  155.12     .06       0   409.5    .045       0   433.4     .06       0
  512.94     .12       0
#XS Ineff= 2 , 0
          284.45 1688.57
Permanent Ineff=
       F       F
Bank Sta=409.5,433.4
XS Rating Curve= 0 ,0
Exp/Cntr=0.3,0.1