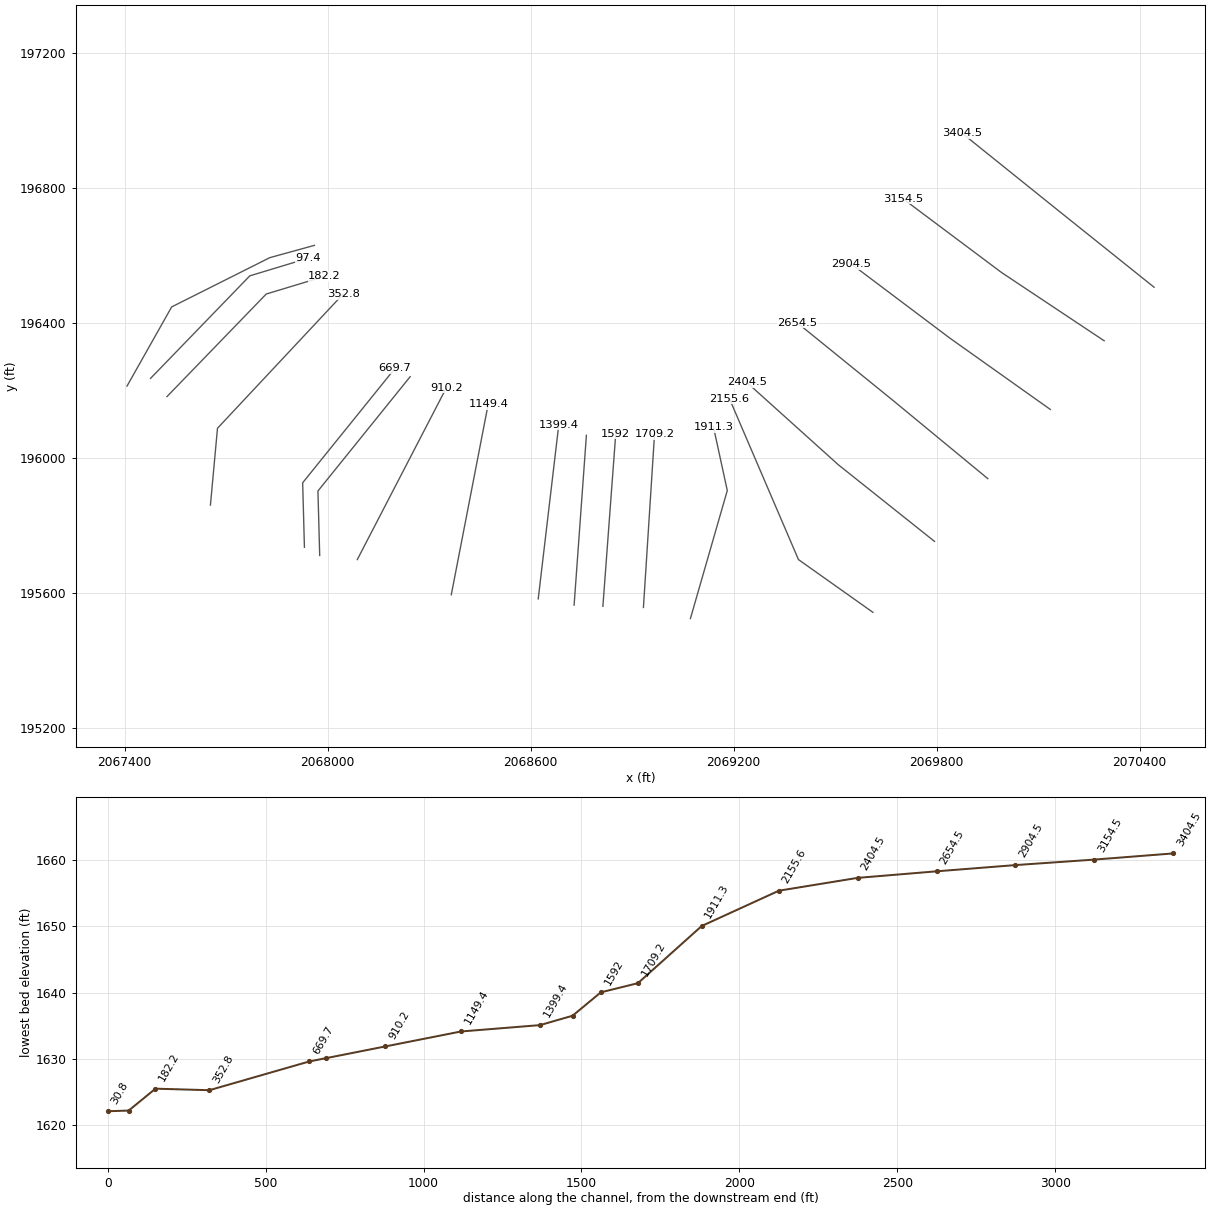
HEC-RAS study INDIANCKT2.prj: INDIANCKT2

--- INDIANCKT2.g01 (geometry) --- (continued)

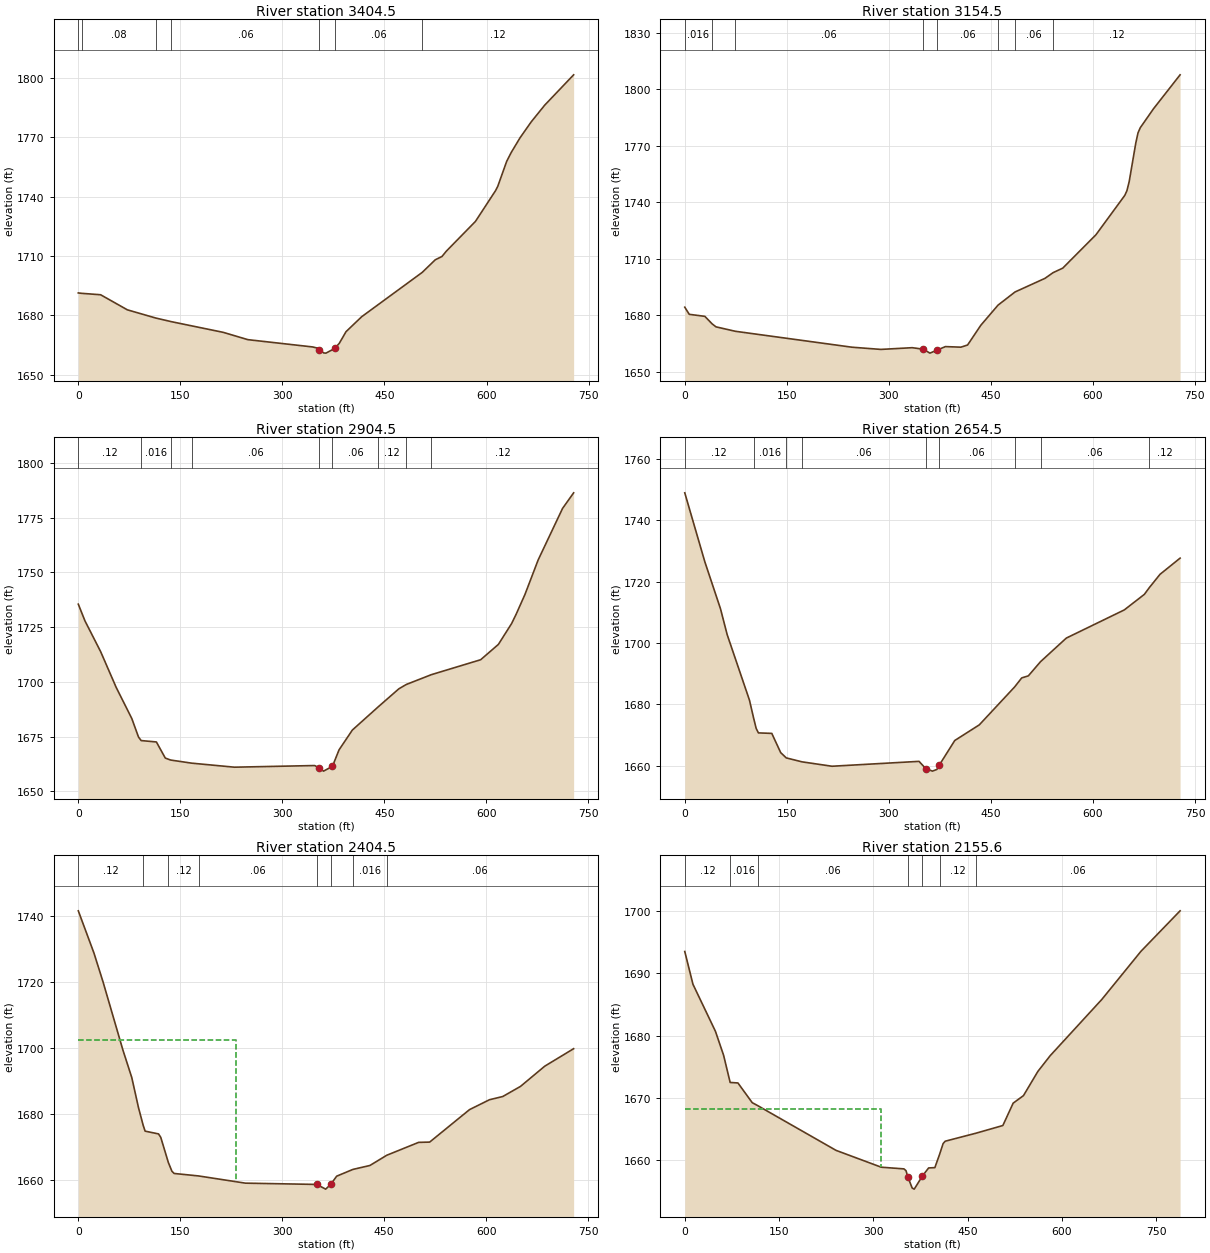
Type RM Length L Ch R = 1 ,3404.5  ,247.9,250,250.7
XS GIS Cut Line= 3
     2070442.371      196505.651     2070158.472      196733.406
     2069874.944      196961.818
#Sta/Elev= 30
       0  1691.4    4.851691.207    32.8 1690.48    72.1 1682.86  113.75 1678.72
  136.951676.862   213.1 1671.47   249.2 1667.78   344.3  1664.1   350.8 1663.57
   354.1 1662.71   360.7 1661.06     364 1660.97   377.1 1663.37   383.6 1665.94
   393.5 1671.82   416.4 1679.35   505.51701.798   524.7 1708.18   534.5 1709.83
   541.1  1712.6   583.7 1727.56   613.2  1743.1   616.5  1745.3   629.6 1757.92
   636.2 1762.37   649.3 1769.88   665.7 1777.91   685.4 1786.31     728 1801.68
#Mann= 7 ,-1 , 0
       0    .016       0    4.85     .08       0  113.75     .12       0
  136.95     .06       0   354.1    .045       0   377.1     .06       0
   505.5     .12       0
Bank Sta=354.1,377.1
XS Rating Curve= 0 ,0
Exp/Cntr=0.3,0.1

Type RM Length L Ch R = 1 ,3154.5  ,250.3,250,249.6
XS GIS Cut Line= 3
     2070294.885      196347.019     2069992.118      196548.864
     2069700.358       196767.65
#Sta/Elev= 30
       0  1684.4     6.6 1680.62    29.5 1679.55   40.291675.546    45.9 1673.98
   74.381671.628   245.9 1663.18   288.5 1662.01   334.4 1662.92   350.8 1662.14
   360.6 1660.04   371.4 1661.68   383.4  1663.5   406.2  1663.2     416 1664.35
   435.5 1674.83   460.81685.499  485.791692.475   529.9 1699.71  541.671702.706
     556 1705.12   604.8 1722.81   647.2 1743.68   650.4  1746.2   653.7 1750.97
   663.4 1771.41   666.7 1776.86     670 1779.58   689.5 1789.66   728.6 1807.65
#Mann= 8 ,-1 , 0
       0    .016       0   40.29     .12       0   74.38     .06       0
   350.8    .045       0   371.4     .06       0   460.8     .12       0
  485.79     .06       0  541.67     .12       0
Bank Sta=350.8,371.4
XS Rating Curve= 0 ,0
Exp/Cntr=0.3,0.1

Type RM Length L Ch R = 1 ,2904.5  ,251.6,250,249.1
XS GIS Cut Line= 3
     2070135.633      196143.745       2069839.1      196354.698
      2069548.16      196574.042
#Sta/Elev= 30
       0 1735.48     9.8 1727.84    32.8 1713.83    55.7 1697.46    78.7 1683.21
    88.5  1674.8    92.41673.171   114.8 1672.54   127.9 1665.18   135.71664.275
  167.031662.839   229.5 1661.01   347.5 1661.76   354.1 1660.73   360.6 1659.21
   373.7 1661.41   383.4 1668.93     403 1677.99  441.271688.659   471.3 1696.81
  482.291698.801  519.161703.283   591.6  1710.1   617.7 1717.11   637.2 1726.68
   643.7 1730.83   656.7 1739.89   676.2 1755.72     712 1779.22   728.3 1786.35
#Mann= 9 ,-1 , 0
       0     .12       0    92.4    .016       0   135.7     .12       0
  167.03     .06       0   354.1    .045       0   373.7     .06       0
  441.27     .12       0  482.29    .016       0  519.16     .12       0
Bank Sta=354.1,373.7
XS Rating Curve= 0 ,0
Exp/Cntr=0.3,0.1

Type RM Length L Ch R = 1 ,2654.5  ,249.6,250,248.8
XS GIS Cut Line= 3
     2069951.051      195938.709     2069670.487      196170.639
     2069387.985      196400.174
#Sta/Elev= 30
       0  1748.9    29.5 1726.43    52.5 1711.14    62.3 1702.74    95.1 1681.37
  101.031675.686   104.9  1672.2   108.2 1670.72   127.9 1670.56     141 1664.29
  149.231662.573  172.241661.295   216.4 1659.86   344.3 1661.45   354.2 1659.09
     364 1658.27   370.6 1658.82   373.8 1660.14   396.8 1668.24   432.9 1673.34
   484.81685.681   495.2 1688.62     505  1689.3  522.931693.926   560.8  1701.6
     646 1710.77   675.5 1715.84  682.681718.003   698.5 1722.36     728 1727.63
#Mann= 9 ,-1 , 0
       0     .12       0  101.03    .016       0  149.23     .12       0
  172.24     .06       0   354.2    .045       0   373.8     .06       0
   484.8    .016       0  522.93     .06       0  682.68     .12       0
Bank Sta=354.2,373.8
XS Rating Curve= 0 ,0
Exp/Cntr=0.3,0.1

Type RM Length L Ch R = 1 ,2404.5  ,260.3,248.9,238
XS GIS Cut Line= 3
     2069793.478      195752.929     2069509.133      195979.955
      2069238.24      196224.282
#Sta/Elev= 30
       0 1741.55      23 1728.78    36.1 1720.23    65.6 1699.41    78.7 1691.05
    88.5 1681.99   95.441676.609    98.3 1674.84     118    1674   121.3 1672.96
  132.471665.348   137.7 1662.71     141 1662.02  176.951661.271   245.8 1659.09
   350.8  1658.7   363.9 1657.28   371.4 1658.72   380.1  1661.2  403.991663.249
     429 1664.44  453.821667.538   500.7 1671.44   516.9 1671.52   575.6 1681.36
   604.9 1684.35   624.4 1685.32   650.5 1688.38   686.3 1694.52   728.7  1699.8
#Mann= 8 ,-1 , 0
       0     .12       0   95.44    .016       0  132.47     .12       0
  176.95     .06       0   350.8    .045       0   371.4     .06       0
  403.99    .016       0  453.82     .06       0
#XS Ineff= 2 , 0
          231.54 1702.57
Permanent Ineff=
       F       F
Bank Sta=350.8,371.4
XS Rating Curve= 0 ,0
Exp/Cntr=0.3,0.1

Type RM Length L Ch R = 1 ,2155.6  ,259,244.3,228.8
XS GIS Cut Line= 3
     2069611.561      195542.772     2069391.427      195699.051
     2069187.531      196175.387
#Sta/Elev= 30
       0 1693.49      13 1688.24    48.8 1680.68    61.8 1676.83   72.211672.472
    84.6 1672.39   107.3 1669.23  115.92 1668.76   240.7 1661.57   312.6 1658.87
   348.7  1658.6     352 1658.31   355.2 1657.23   361.8 1655.53   365.1 1655.35
   378.2 1657.47     388 1658.75   397.9  1658.8  405.361660.911     411 1662.65
   414.3 1663.04  462.741664.311   506.1 1665.56   522.5 1669.15   538.9 1670.36
   561.8 1674.24   581.5 1676.78   663.5 1685.79   725.8 1693.52   788.1 1700.02
#Mann= 7 ,-1 , 0
       0     .12       0   72.21    .016       0  115.92     .06       0
   355.2    .045       0   378.2    .016       0  405.36     .12       0
  462.74     .06       0
#XS Ineff= 2 , 0
          312.04 1668.21
Permanent Ineff=
       F       F
Bank Sta=355.2,378.2
XS Rating Curve= 0 ,0
Exp/Cntr=0.3,0.1

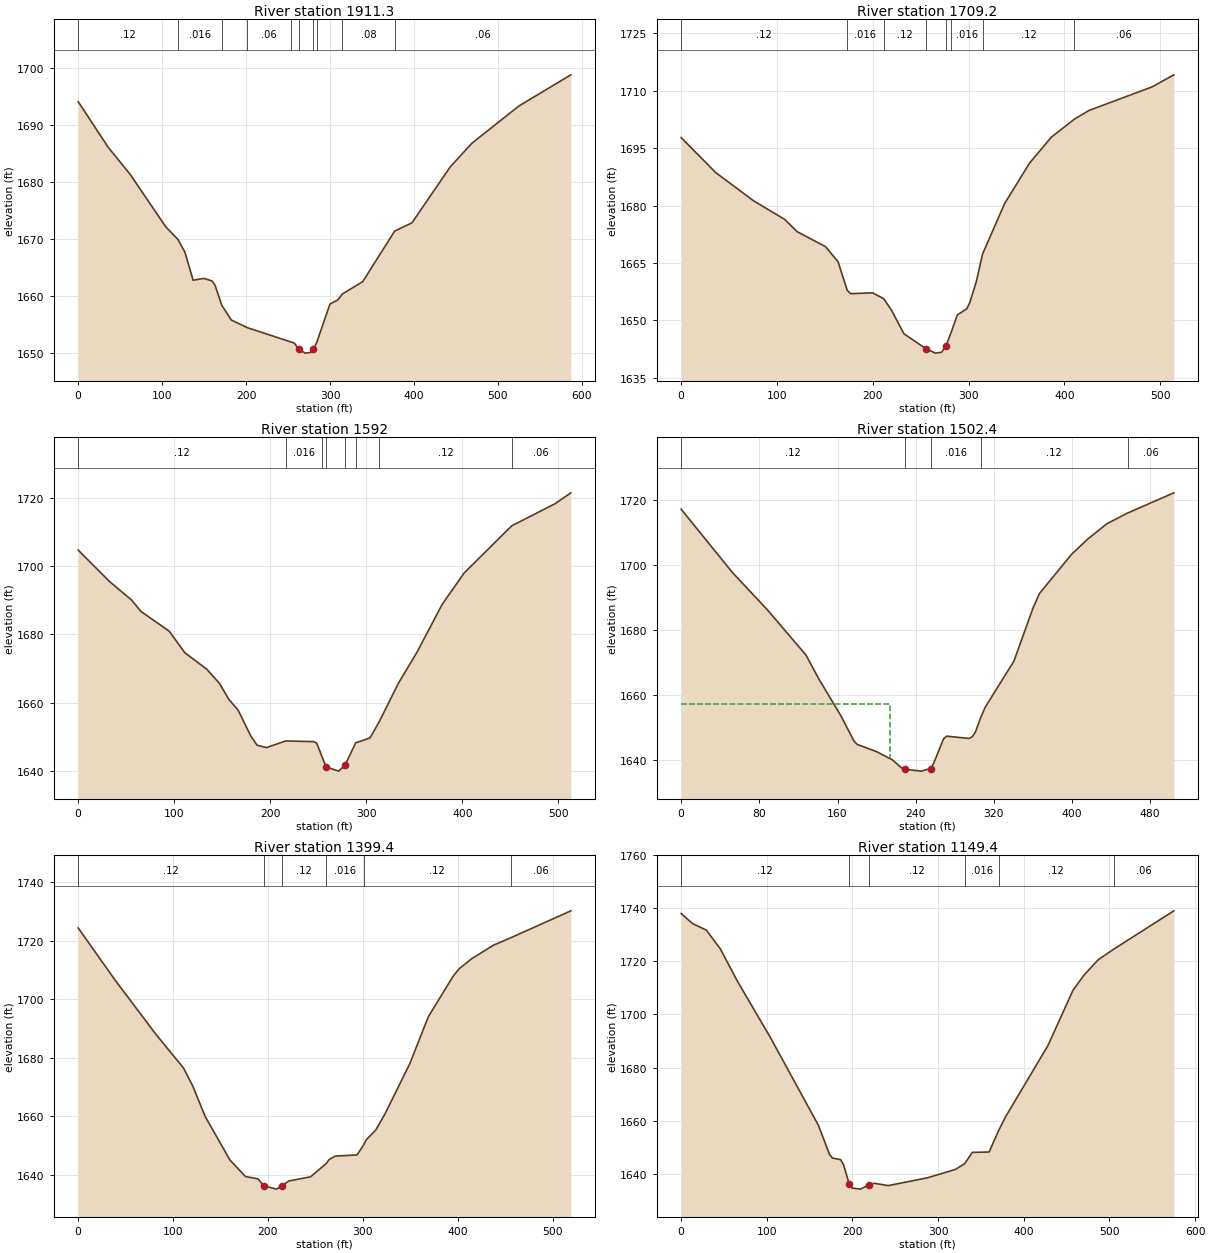
Type RM Length L Ch R = 1 ,1911.3  ,197.2,202.1,206.7
XS GIS Cut Line= 3
     2069072.143      195524.475      2069181.05      195903.541
      2069140.29      196091.641
#Sta/Elev= 30
       0 1694.07    35.8 1686.06    61.9 1681.34   104.3 1672.16  118.781669.948
   127.1 1667.73   136.9  1662.8   149.9 1663.11   159.7 1662.65     163 1661.94
  171.191658.386   182.5 1655.82  201.491654.492  253.281651.994   257.5 1651.79
   262.9 1650.68   270.5 1650.03   277.1 1650.15   280.3 1650.71  284.011651.828
   299.9 1658.61   309.6 1659.38  314.75 1660.39     339 1662.55  377.041671.401
   397.7 1672.86   443.3 1682.66   469.4 1686.83   524.9 1693.29   586.9 1698.76
#Mann= 10 ,-1 , 0
       0     .12       0  118.78    .016       0  171.19     .12       0
  201.49     .06       0  253.28     .12       0   262.9    .045       0
   280.3     .12       0  284.01    .016       0  314.75     .08       0
  377.04     .06       0
Bank Sta=262.9,280.3
XS Rating Curve= 0 ,0
Exp/Cntr=0.3,0.1

Type RM Length L Ch R = 1 ,1709.2  ,117.7,117.3,117
XS GIS Cut Line= 2
     2068933.238      195557.225      2068966.08      196070.579
#Sta/Elev= 30
       0 1697.76      36 1688.63    75.4 1681.27   108.1 1676.36   121.2 1673.15
   150.7 1669.25   163.8  1665.3   173.41657.804   176.9 1656.96   199.9 1657.17
  211.381655.672   219.5 1652.68   232.6 1646.46   255.6 1642.57   265.4 1641.41
     272 1641.64   276.5 1643.32  282.131646.997   288.3  1651.4   298.2    1653
   301.4 1654.67     308 1659.97   314.71667.337   337.5 1680.42   363.7 1691.08
   386.6  1697.9  410.481702.571   425.9 1704.87   491.5    1711   514.4 1714.17
#Mann= 8 ,-1 , 0
       0     .12       0   173.4    .016       0  211.38     .12       0
   255.6    .045       0   276.5     .12       0  282.13    .016       0
   314.7     .12       0  410.48     .06       0
Bank Sta=255.6,276.5
XS Rating Curve= 0 ,0
Exp/Cntr=0.3,0.1

Type RM Length L Ch R = 1 ,1592    ,89.5,89.6,89.5
XS GIS Cut Line= 2
     2068813.447      195560.697     2068851.496      196072.315
#Sta/Elev= 30
       0 1704.66    32.7 1695.46    55.6 1690.05    65.4 1686.72    94.8 1680.94
   111.1 1674.64     134  1669.8     147 1665.73   156.8 1661.06   166.6 1657.83
   179.7 1650.33   186.3  1647.6   196.1 1646.92  216.111648.851   245.1 1648.66
   248.4  1648.2  254.261643.994   258.2 1641.26   271.2 1640.03   277.8 1641.73
  288.971648.311   303.9 1649.73  313.511654.491   333.3 1665.65   352.9 1674.85
     379 1688.78   401.9 1697.97  451.431711.748   496.7 1718.24     513  1721.4
#Mann= 8 ,-1 , 0
       0     .12       0  216.11    .016       0  254.26     .12       0
   258.2    .045       0   277.8     .12       0  288.97    .016       0
  313.51     .12       0  451.43     .06       0
Bank Sta=258.2,277.8
XS Rating Curve= 0 ,0
Exp/Cntr=0.3,0.1

Type RM Length L Ch R = 1 ,1502.4  ,103.9,103,102.3
XS GIS Cut Line= 2
     2068728.377      195564.169     2068764.691      196067.106
#Sta/Elev= 30
       0 1717.08    52.4 1697.63    88.4 1686.07   127.7 1672.22   140.8  1664.9
   163.7  1653.4   176.8 1645.77   180.1 1644.73   199.7 1642.52   216.1 1639.99
   225.9 1637.42   229.2 1637.08   245.6  1636.5   255.4  1637.3   258.7 1639.14
   268.5 1646.45   271.8 1647.26   294.7 1646.54     298 1647.12   301.2 1648.57
  306.551653.006   311.1 1656.14   340.5 1670.33   360.2 1686.78   366.7 1691.16
   399.5 1703.19   415.8 1707.83   435.5 1712.58  456.771715.884   504.2 1722.12
#Mann= 5 ,-1 , 0
       0     .12       0   229.2    .045       0   255.4    .016       0
  306.55     .12       0  456.77     .06       0
#XS Ineff= 2 , 0
          213.34 1657.14
Permanent Ineff=
       F       F
Bank Sta=229.2,255.4
XS Rating Curve= 0 ,0
Exp/Cntr=0.3,0.1

Type RM Length L Ch R = 1 ,1399.4  ,250.7,250,247
XS GIS Cut Line= 2
      2068622.33      195582.731     2068683.094      196098.356
#Sta/Elev= 30
       0 1724.43    39.2 1706.46    81.6 1688.18     111 1676.53   120.8 1670.31
   133.9  1659.9     160 1645.02   176.3  1639.4   189.4 1638.61   195.9 1636.21
     209 1635.09   214.4 1636.19     222 1637.88   244.9  1639.3  261.451643.861
   264.5 1645.22     271  1646.4   293.9 1646.78  301.021650.333   303.7 1652.03
   313.5 1655.24   323.3  1660.8   349.4 1677.95     369 1694.04   395.1  1707.9
   401.6  1710.5   414.7  1713.9   437.6 1718.51  455.671721.036   519.2 1730.28
#Mann= 6 ,-1 , 0
       0     .12       0   195.9    .045       0   214.4     .12       0
  261.45    .016       0  301.02     .12       0  455.67     .06       0
Bank Sta=195.9,214.4
XS Rating Curve= 0 ,0
Exp/Cntr=0.3,0.1

Type RM Length L Ch R = 1 ,1149.4  ,245.1,239.2,232.1
XS GIS Cut Line= 2
     2068365.385      195594.884      2068474.58       196159.64
#Sta/Elev= 30
       0 1738.09    13.1 1734.32    29.4 1731.82    45.8 1724.71    65.4 1712.71
   104.6 1691.07   160.2 1658.21   173.2 1647.22   176.5 1645.87   186.3 1645.23
   189.6 1643.27   196.1 1636.22   199.3 1634.55   209.2 1634.13     219 1635.76
   225.5 1636.34   241.8 1635.46   287.6 1638.41   320.3 1641.58  331.011643.741
   339.9 1647.99   359.5 1648.13  370.891656.412   379.1 1661.63   428.1 1688.23
   457.6 1709.24   470.6 1714.97     487 1720.68  504.95 1724.63   575.2  1739.1
#Mann= 6 ,-1 , 0
       0     .12       0   196.1    .045       0     219     .12       0
  331.01    .016       0  370.89     .12       0  504.95     .06       0
Bank Sta=196.1,219
XS Rating Curve= 0 ,0
Exp/Cntr=0.3,0.1

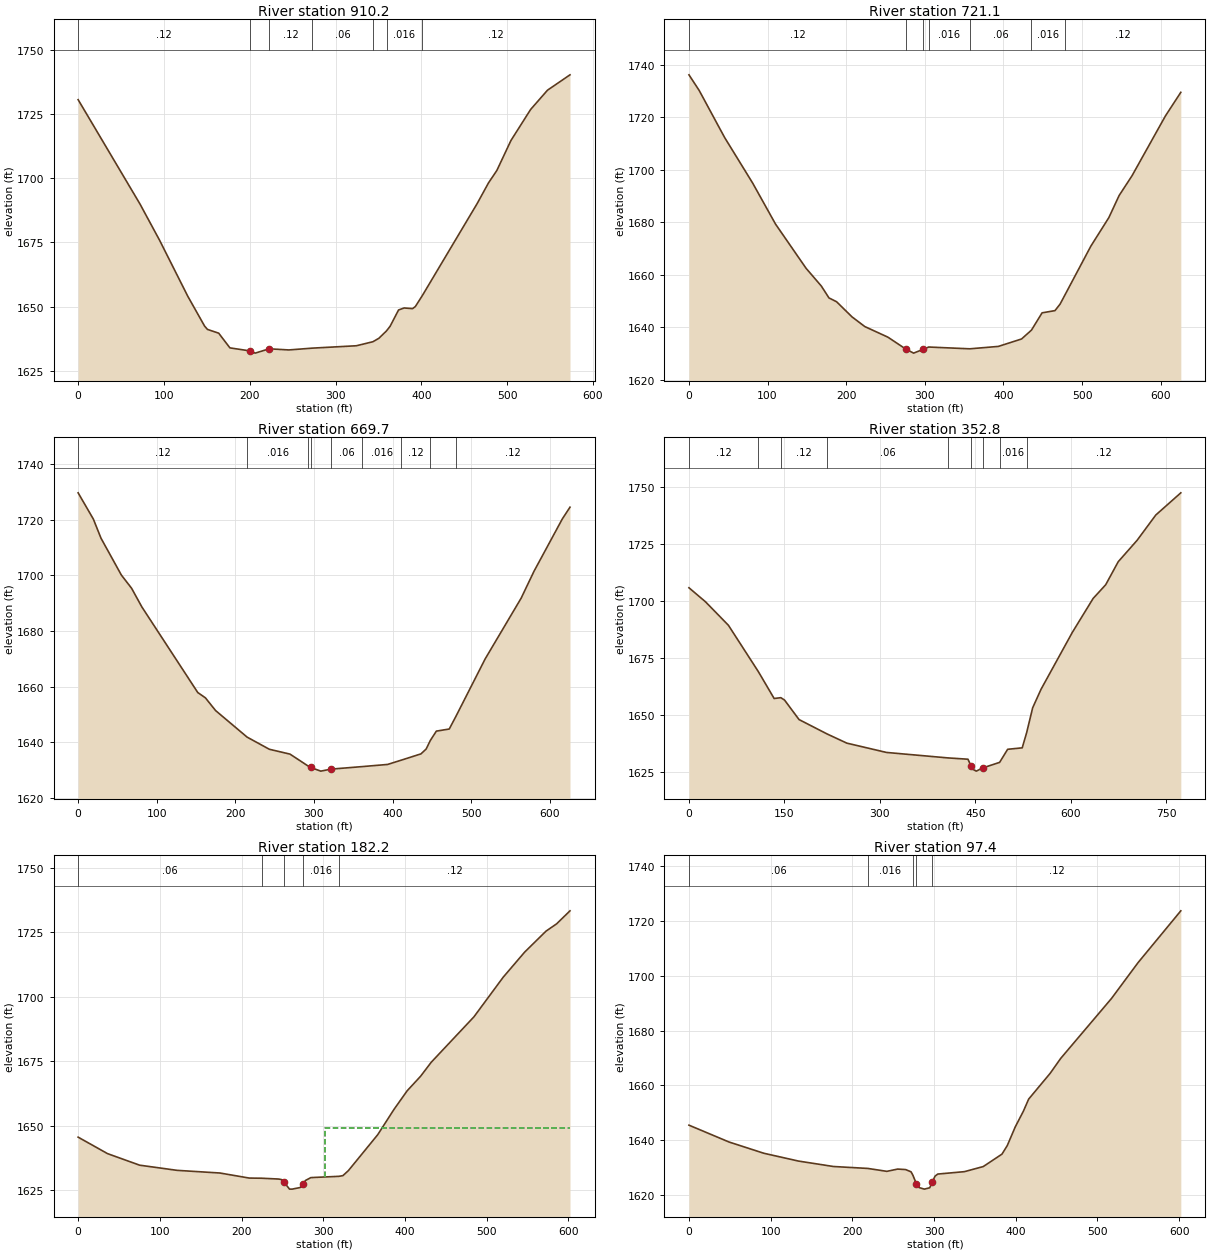
Type RM Length L Ch R = 1 ,910.2   ,193,189.1,183.9
XS GIS Cut Line= 2
     2068087.608      195699.051     2068351.005      196208.126
#Sta/Elev= 30
       0 1730.58    72.1 1689.94      95 1675.79   127.7 1654.08   147.4  1642.4
   150.7 1641.12   163.8 1639.65   176.9 1633.92   200.2 1632.75   206.3 1631.88
   222.7 1633.56   245.6 1633.12  273.011633.827   324.3 1634.75  343.541636.321
   350.5 1637.66  359.37 1640.55   363.6 1642.36   373.4 1648.68   379.9 1649.46
   389.8 1649.21     393 1650.03  401.221654.344   465.1 1690.17   478.2 1698.16
     488 1703.04   504.4 1714.69   527.3 1726.76     547 1734.28   573.2 1740.26
#Mann= 7 ,-1 , 0
       0     .12       0   200.2    .045       0   222.7     .12       0
  273.01     .06       0  343.54     .12       0  359.37    .016       0
  401.22     .12       0
Bank Sta=200.2,222.7
XS Rating Curve= 0 ,0
Exp/Cntr=0.3,0.1

Type RM Length L Ch R = 1 ,721.1   ,51.7,51.4,51.7
XS GIS Cut Line= 3
     2067976.496      195711.204     2067971.288      195902.176
     2068243.858      196240.717
#Sta/Elev= 30
       0 1736.15      13  1730.2    45.3  1712.3      81 1694.92   110.1 1679.29
     149 1662.42   168.4 1655.66   178.1 1651.14   187.8 1649.68   207.4 1643.92
   223.7 1640.22   253.1 1636.18     276 1631.61   285.8  1630.1   297.7 1631.52
  305.041632.424  357.251631.743   393.6 1632.66   423.1 1635.49  435.741638.879
   449.2 1645.45   465.6  1646.3   472.1 1648.77  478.651652.468   511.3 1670.89
   534.2 1681.77   547.2 1690.15   563.6 1697.68   606.1 1720.48   625.7 1729.49
#Mann= 7 ,-1 , 0
       0     .12       0     276    .045       0   297.7     .12       0
  305.04    .016       0  357.25     .06       0  435.74    .016       0
  478.65     .12       0
Bank Sta=276,297.7
XS Rating Curve= 0 ,0
Exp/Cntr=0.3,0.1

Type RM Length L Ch R = 1 ,669.7   ,316.2,316.9,314.5
XS GIS Cut Line= 3
     2067931.358      195735.509     2067926.149      195926.481
     2068198.719      196265.023
#Sta/Elev= 30
       0 1729.67    19.4 1720.21    29.1 1713.35      55 1700.11      68 1695.36
      81 1688.68   152.2 1657.87   161.9 1655.97   174.8 1651.41  214.911641.856
   243.3 1637.47   269.5 1635.74  292.711631.429   295.6 1630.95   308.7 1629.62
   321.8 1630.34  361.55 1631.25   393.6 1632.02  410.461633.509   436.1 1635.82
   442.7 1637.56  448.051640.651   455.7    1644   472.1 1644.76  480.611649.316
   517.8 1669.97   563.6 1691.82   579.9 1701.46   615.9 1720.27   625.7 1724.51
#Mann= 9 ,-1 , 0
       0     .12       0  214.91    .016       0  292.71     .06       0
   295.6    .045       0   321.8     .06       0  361.55    .016       0
  410.46     .12       0  448.05    .016       0  480.61     .12       0
Bank Sta=295.6,321.8
XS Rating Curve= 0 ,0
Exp/Cntr=0.3,0.1

Type RM Length L Ch R = 1 ,352.8   ,171,170.6,169.5
XS GIS Cut Line= 3
      2067653.58      195860.509     2067674.413       196087.94
     2068045.941      196485.509
#Sta/Elev= 30
       0 1705.68    26.1  1699.5      62 1689.22   109.11668.861   133.8 1657.12
  144.231657.492   150.1 1656.45   172.9 1647.89  216.961641.574     248 1637.55
   310.3 1633.47  406.09 1631.09   438.2  1630.5     443  1627.6   444.7 1626.24
   451.3 1625.28   461.1 1626.66  487.911629.117   500.5 1634.85   523.4 1635.49
  530.421642.205   539.8 1653.04   552.9 1661.13   602.1 1686.11   634.8    1701
   654.5    1707   674.2  1717.1   703.7 1726.44   733.2 1737.58   772.5 1747.31
#Mann= 9 ,-1 , 0
       0     .12       0   109.1    .016       0  144.23     .12       0
  216.96     .06       0  406.09     .12       0     443    .045       0
   461.1     .12       0  487.91    .016       0  530.42     .12       0
Bank Sta=443,461.1
XS Rating Curve= 0 ,0
Exp/Cntr=0.3,0.1

Type RM Length L Ch R = 1 ,182.2   ,80.8,84.8,84.5
XS GIS Cut Line= 3
     2067525.108       196181.69      2067818.51      196485.509
     2067990.385      196537.592
#Sta/Elev= 30
       0 1645.63      36 1639.25    75.3 1634.78   121.1 1632.78   173.5 1631.75
   209.5 1629.79   224.6 1629.73   245.6 1629.41   248.8 1629.21   252.1 1628.17
   258.7 1625.52   261.9 1625.51   271.8 1626.13     275 1627.51   278.3 1628.87
   284.8 1629.97  319.131630.463   324.1 1630.74   330.7 1632.65   366.7 1646.59
   386.4 1656.29   402.7 1663.58   419.1 1669.19   432.2 1674.64   484.4  1692.2
   520.3 1707.57   546.4 1717.23   572.6 1725.37   585.6 1728.21     602 1733.25
#Mann= 5 ,-1 , 0
       0     .06       0   224.6     .12       0   252.1    .045       0
     275    .016       0  319.13     .12       0
#XS Ineff= 2 , 0
                          302.32            1649
Permanent Ineff=
       F       F
Bank Sta=252.1,275
XS Rating Curve= 0 ,0
Exp/Cntr=0.3,0.1

Type RM Length L Ch R = 1 ,97.4    ,78.3,66.6,58.6
XS GIS Cut Line= 3
     2067476.496      196235.509     2067769.899      196539.329
     2067941.774      196591.412
#Sta/Elev= 30
       0 1645.53    49.1 1639.38    91.7 1635.28   134.2 1632.43   176.8 1630.46
     219 1629.75   242.3 1628.69   255.4 1629.52   265.2 1629.34   271.8 1628.52
  273.971627.354   278.3 1624.21   281.6 1622.78   288.1 1622.21   294.7 1622.71
     298 1624.94   301.2 1626.95   304.5  1627.7   337.2 1628.58   360.2 1630.44
   383.1 1634.97   389.6 1638.09   399.4 1644.92   409.3 1650.61   415.8 1655.04
     442 1664.39     455 1669.87   517.1 1691.69   549.7 1704.79     602 1723.66
#Mann= 5 ,-1 , 0
       0     .06       0     219    .016       0  273.97     .12       0
   278.3    .045       0     298     .12       0
Bank Sta=278.3,298
XS Rating Curve= 0 ,0
Exp/Cntr=0.3,0.1

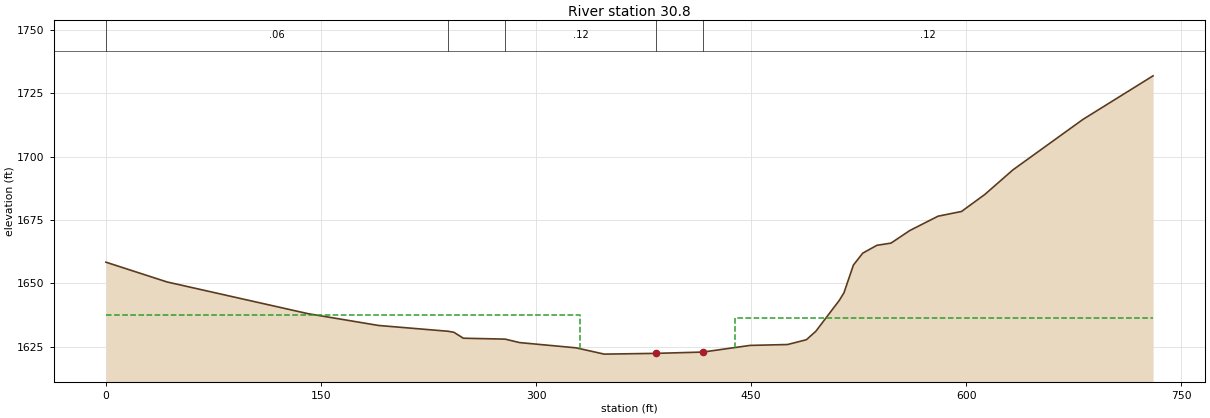
Type RM Length L Ch R = 1 ,30.8    ,36,30.8,25.6
XS GIS Cut Line= 4
     2067407.052       196212.94     2067538.996      196447.315
     2067828.927      196593.148     2067960.871      196629.606
#Sta/Elev= 30
       0  1658.4    42.6  1650.6     141 1638.07   190.2 1633.42  238.591631.138
   242.7 1630.74   249.3 1628.39  278.47 1628.03   288.6 1626.66     328 1624.59
   347.6 1622.11   383.7 1622.41   416.5 1622.93   449.3 1625.55   475.5  1625.9
   488.6  1627.8   495.2 1631.14   511.6 1643.36   514.8 1646.32   521.4 1657.27
   527.9 1661.96   537.8 1665.06   547.6 1665.92   560.7 1670.88   580.4 1676.54
   596.8 1678.41   613.1 1685.14   632.6  1694.8   681.5 1714.74   730.4 1731.94
#Mann= 5 ,-1 , 0
       0     .06       0  238.59    .016       0  278.47     .12       0
   383.7    .045       0   416.5     .12       0
#XS Ineff= 2 , 0
          331.03 1637.71  438.67         1636.43
Permanent Ineff=
       F       F
Bank Sta=383.7,416.5
XS Rating Curve= 0 ,0
Exp/Cntr=0.3,0.1

Chan Stop Cuts=-1
Use User Specified Reach Order=0
Composite Channel Slope=5